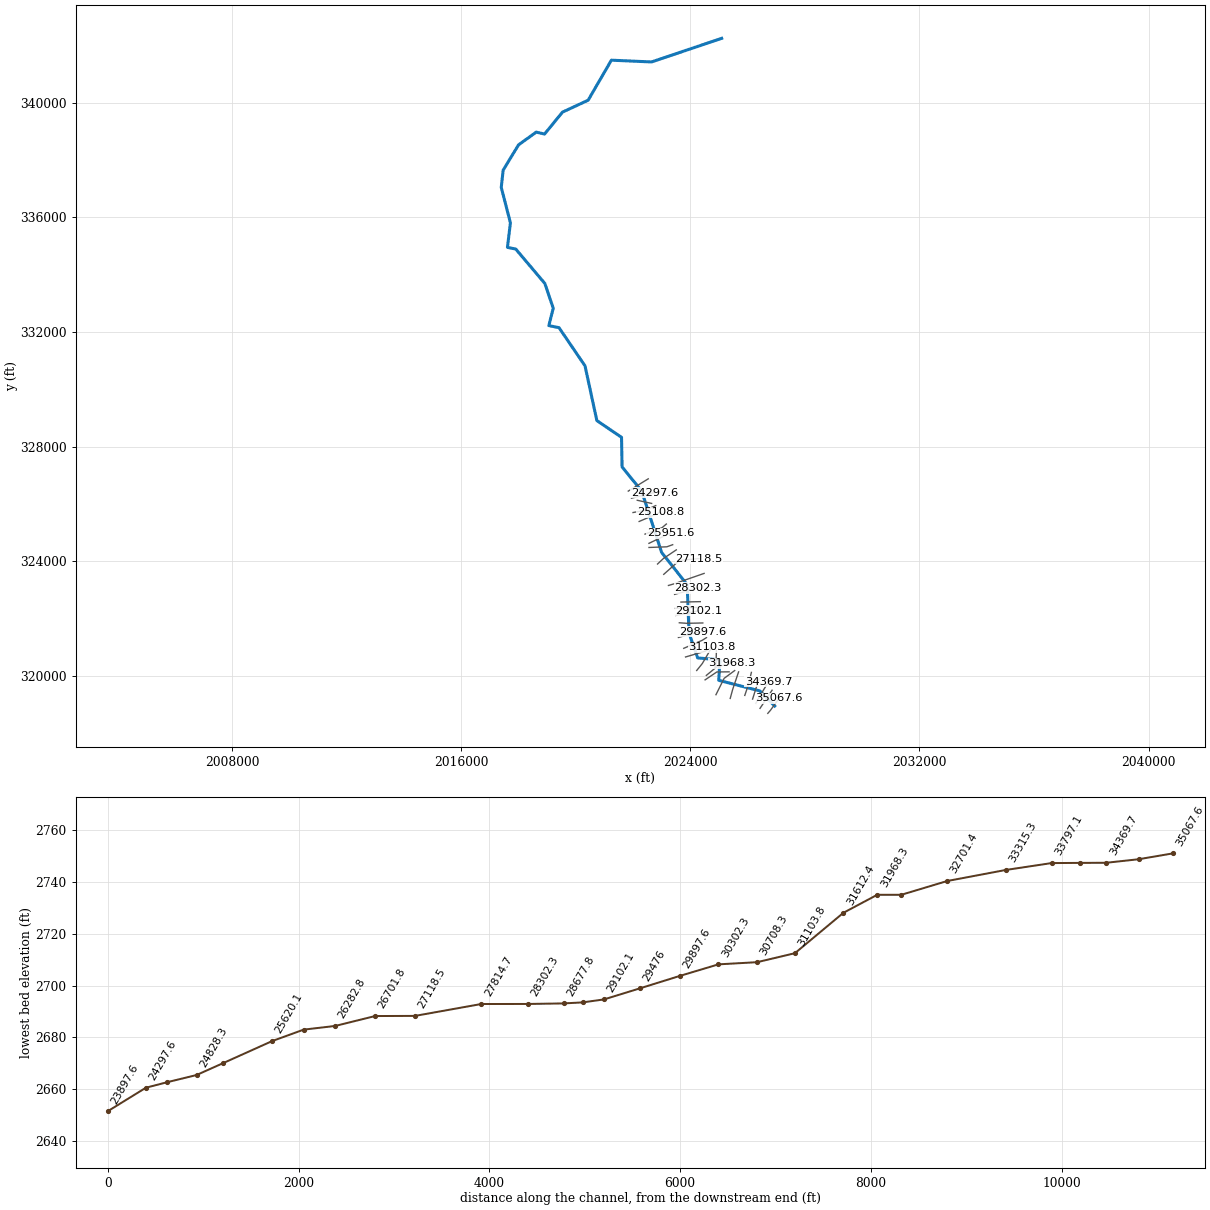
--- SewellCrk.prj (project) ---

Proj Title=SewellCrk
Current Plan=p01
Default Exp/Contr=0,0
English Units
Geom File=g01
Flow File=f01
Plan File=p01
BEGIN DESCRIPTION:
END DESCRIPTION:
DSS Export Rating Curves= 0
DSS Export Rating Curve Sorted= 0
DSS Export Volume Flow Curves= 0
DXF OffsetX= 0
DXF OffsetY= 0
DXF ScaleX= 0
DXF ScaleY= 0

--- SewellCrk.p01 (plan) ---

Plan Title=Floodplain
Program Version=4.00
Geom File=g01
Flow File=f01
K Sum by GR=0
Std Step Tol=0.01
Critical Tol=0.01
Num of Std Step Trials=20
Max Error Tol=0.3
Flow Tol Ratio=0.001
Split Flow NTrial=30
Split Flow Tol=0.02
Split Flow Ratio=0.02
Log Output Level=0
Friction Slope Method=1
Unsteady Friction Slope Method=2
Unsteady Bridges Friction Slope Method=1
Global Log Level=0
CheckData=False
Run HTab=0
Run UNet=0
Run PostProcess=0
UNET Theta=0
UNET Theta Warmup=0
UNET ZTol=0
UNET ZSATol=0
UNET MxIter=0
UNET MaxInSteps=0
UNET DtIC=0
UNET DtMin=0
UNET MaxCRTS=0
UNET WFStab=0
UNET SFStab=0
UNET WFX=0
UNET SFX=0
UNET DSS MLevel=0
UNET DZMax Abort=0
UNET Convert EG Bridges=0
UNET Use Existing IB Tables=0
UNET Froude Limit=0
UNET Froude Power=0
Write IC File=0
Echo Input=False
Echo Output=False
Write Detailed=0

--- SewellCrk.f01 (steady flow) ---

Flow Title=NFF Regression Equation
Program Version=4.10
Number of Profiles= 1
Profile Names=P100yr
River Rch & RM=SewellCrk,Main            ,35067.6
452.2453
River Rch & RM=SewellCrk,Main            ,34709.4
639.2871
River Rch & RM=SewellCrk,Main            ,32221.3
709.3621
River Rch & RM=SewellCrk,Main            ,30302.3
754.5719
River Rch & RM=SewellCrk,Main            ,27814.7
 819.862
River Rch & RM=SewellCrk,Main            ,27118.5
932.8365
River Rch & RM=SewellCrk,Main            ,26701.8
937.7236
River Rch & RM=SewellCrk,Main            ,24519
1040.709
River Rch & RM=SewellCrk,Main            ,23106.9
1123.962
River Rch & RM=SewellCrk,Main            ,19449.1
1243.815
River Rch & RM=SewellCrk,Main            ,17393.5
1342.689
River Rch & RM=SewellCrk,Main            ,12297.6
1476.613
River Rch & RM=SewellCrk,Main            ,11364.8
1621.288
River Rch & RM=SewellCrk,Main            ,10656.7
 1795.74
River Rch & RM=SewellCrk,Main            ,4007.6
1959.556
River Rch & RM=SewellCrk,Main            ,3555.5
2200.039
River Rch & RM=SewellCrk,Main            ,297.6
2270.832
Boundary for River Rch & Prof#=SewellCrk,Main            , 1
Up Type= 0
Dn Type= 3
Dn Slope=0.000453
DSS Import GetInterval= 0
DSS Import GetPeak= 0
DSS Import FillOption= 0

--- SewellCrk.g01 (geometry) ---

Geom Title=USGS 3m DEM
Program Version=4.10

River Reach=SewellCrk       ,Main
Reach XY= 30
     2026946.674      318953.194     2026431.049      319479.235
     2024993.549      319849.027     2025036.952      320560.833
      2024258.96      320629.205     2023957.091      321498.332
     2023893.489      323181.726     2023000.494      324309.097
     2022306.049      326447.117     2021620.285      327290.867
     2021601.188      328322.117     2020740.242      328907.682
     2020326.882      330815.173     2019419.202      332148.124
     2019064.729      332219.687     2019217.507      332827.326
     2018924.104      333690.173     2017909.284      334889.369
     2017618.384      334948.239     2017722.716       335803.02
     2017402.752      337041.944     2017469.625      337640.326
     2018005.702      338523.506     2018624.584      338967.806
     2018915.424      338900.242     2019538.688      339664.131
     2020436.257      340080.798     2021247.021      341476.631
     2022651.743      341415.345      2025095.98      342238.784

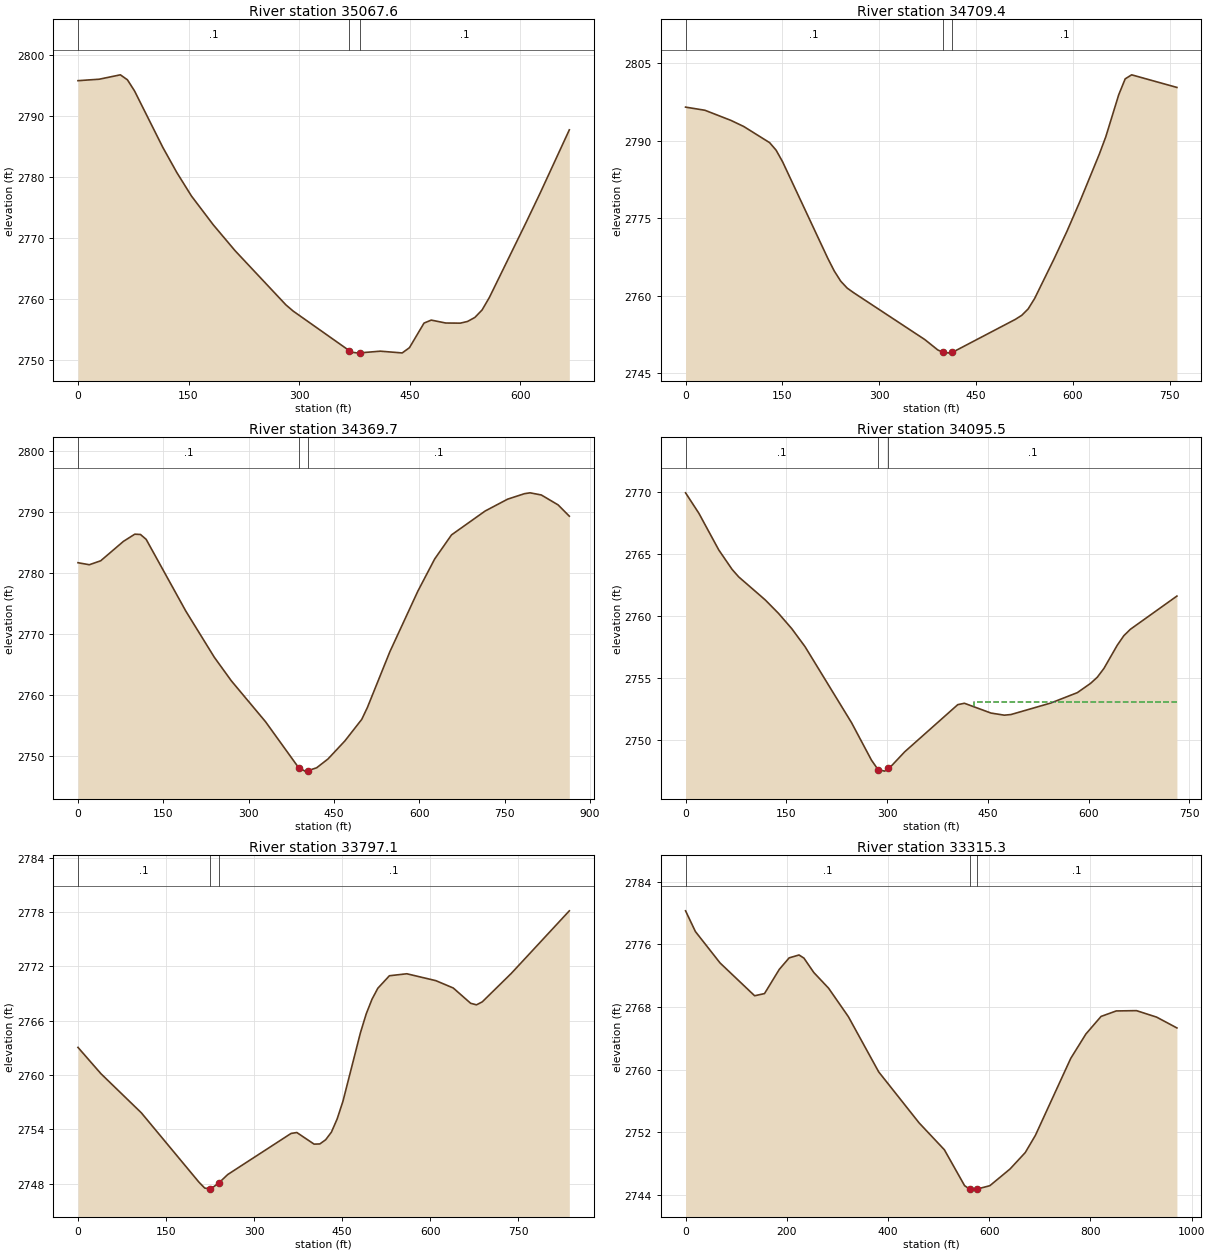
Type RM Length L Ch R = 1 ,35067.6 ,357.5,358.3,357.8
XS GIS Cut Line= 3
     2026706.565       318695.78     2026794.961      318796.804
     2027107.051      319227.957
#Sta/Elev= 30
       0 2795.84    28.8 2796.08    57.5  2796.8    67.1 2795.98    76.7 2794.16
   115.1 2784.89   134.2 2780.74     154  2776.9   183.5 2772.19   213.1 2767.94
   282.1 2759.04   291.9 2758.03   368.2 2751.52   370.8 2751.29   380.6 2751.13
   383.2 2751.18   410.2 2751.45   439.8 2751.16   449.6 2752.02   469.4 2756.06
   479.2 2756.55   498.9 2756.07   518.6 2756.05   528.5 2756.33   538.4 2756.99
   548.2 2758.22   558.1 2760.28   607.4 2772.46   627.1 2777.44   666.5 2787.77
#Mann= 3 , 0 , 0
       0      .1       0   368.2    .045       0   383.2      .1       0
Bank Sta=368.2,383.2
XS Rating Curve= 0 ,0
Exp/Cntr=0.3,0.1

Type RM Length L Ch R = 1 ,34709.4 ,336.7,339.1,341.2
XS GIS Cut Line= 2
     2026435.265      318870.077     2026856.297      319503.968
#Sta/Elev= 30
       0 2796.49      30 2795.88    70.1 2793.93    90.1 2792.74   130.2 2789.61
   140.2 2788.16   150.2 2785.93   220.3 2767.22   230.3 2764.77   240.3  2762.8
   250.3 2761.46   260.3 2760.57   370.5  2751.5   390.5  2749.5   398.1 2749.04
   410.5 2748.87   413.1 2749.01   510.7  2755.4   520.7 2756.19   530.7 2757.44
   540.7 2759.46   570.7  2767.1   590.8 2772.48   610.8 2778.24   640.8 2787.38
   650.8 2790.73   670.9 2798.89   680.9 2801.96   690.9 2802.74     761  2800.3
#Mann= 3 , 0 , 0
       0      .1       0   398.1    .045       0   413.1      .1       0
Bank Sta=398.1,413.1
XS Rating Curve= 0 ,0
Exp/Cntr=0.3,0.1

Type RM Length L Ch R = 1 ,34369.7 ,269.5,274.2,278.9
XS GIS Cut Line= 3
     2026290.593      319049.866     2026513.479      319440.392
     2026729.725      319793.839
#Sta/Elev= 30
       0 2781.68      20 2781.35      40    2782    79.9 2785.18    99.9 2786.36
   109.9 2786.31   119.9 2785.51   189.8 2773.72   239.8 2766.17   269.8  2762.3
   329.8 2755.61   388.6    2748   399.7 2747.51   403.6 2747.56   419.7 2748.06
   439.7 2749.51   469.4 2752.47     499    2756   508.8 2757.92   548.3 2767.06
   597.6 2777.01   627.2 2782.29   656.8 2786.24     716 2790.16   755.5  2792.1
   785.1    2793     795 2793.14   814.7 2792.79   844.3 2791.16     864 2789.31
#Mann= 3 , 0 , 0
       0      .1       0   388.6    .045       0   403.6      .1       0
Bank Sta=388.6,403.6
XS Rating Curve= 0 ,0
Exp/Cntr=0.3,0.1

Type RM Length L Ch R = 1 ,34095.5 ,298.5,298.3,298.1
XS GIS Cut Line= 2
     2026176.192      319193.682     2026396.888      319891.021
#Sta/Elev= 30
       0 2769.94    19.8 2768.29    49.4 2765.33    69.2 2763.76    79.1 2763.15
   118.6 2761.29   138.4  2760.2   158.2 2758.96   177.9 2757.51   247.1 2751.37
   276.8 2748.34   286.6 2747.58   296.5 2747.46   301.6 2747.68   306.4 2747.88
   326.2 2749.02   405.2 2752.83   415.1 2752.94   454.7 2752.15   474.4 2751.98
   484.3 2752.03   543.6 2752.96   583.2  2753.8   602.9 2754.55   612.8 2755.04
   622.7 2755.75   642.5 2757.62   652.4  2758.4   662.2 2758.92   731.4  2761.6
#Mann= 3 , 0 , 0
       0      .1       0   286.6    .045       0   301.6      .1       0
#XS Ineff= 2 , 0
                          429.92         2753.05
Permanent Ineff=
       F       F
Bank Sta=286.6,301.6
XS Rating Curve= 0 ,0
Exp/Cntr=0.3,0.1

Type RM Length L Ch R = 1 ,33797.1 ,481.8,481.7,481.7
XS GIS Cut Line= 3
     2025903.448      319321.916     2026042.187      319730.779
     2026134.258      320125.649
#Sta/Elev= 30
       0 2763.04    39.2 2760.13   107.9 2755.82   206.1 2748.16   215.9 2747.51
   225.2  2747.4   225.7 2747.39   240.2 2748.08   255.1    2749   363.1 2753.54
   372.9 2753.64   402.3 2752.36   412.1 2752.38     422 2752.84   431.8 2753.68
   441.6 2755.14   451.5  2757.1   481.2 2764.64   491.1 2766.74     501 2768.36
   510.9 2769.57   530.6 2770.95   560.3 2771.17   609.8 2770.41   639.4  2769.6
   669.1 2767.91     679 2767.74   688.9 2768.07   738.3 2771.21   837.2 2778.12
#Mann= 3 , 0 , 0
       0      .1       0   225.2    .045       0   240.2      .1       0
Bank Sta=225.2,240.2
XS Rating Curve= 0 ,0
Exp/Cntr=0.3,0.1

Type RM Length L Ch R = 1 ,33315.3 ,615.9,613,610.3
XS GIS Cut Line= 3
     2025395.064      319217.133     2025479.852       319527.42
     2025687.311      320142.581
#Sta/Elev= 30
       0 2780.27    19.5 2777.62    68.2 2773.61   136.5 2769.42     156  2769.7
   185.2 2772.79   204.7 2774.26   224.2 2774.63   233.9 2774.23   253.4 2772.39
   282.7 2770.38   321.7 2766.75   381.6  2759.7   461.5 2753.18   511.4 2749.75
   551.4 2745.16   561.4 2744.72   561.6 2744.72   576.6 2744.74   601.3 2745.16
   641.3  2747.3   671.2 2749.39   691.2 2751.58   761.1 2761.42   791.1 2764.54
     821 2766.78     851 2767.48     891 2767.52   930.9 2766.69   970.9 2765.31
#Mann= 3 , 0 , 0
       0      .1       0   561.6    .045       0   576.6      .1       0
Bank Sta=561.6,576.6
XS Rating Curve= 0 ,0
Exp/Cntr=0.3,0.1

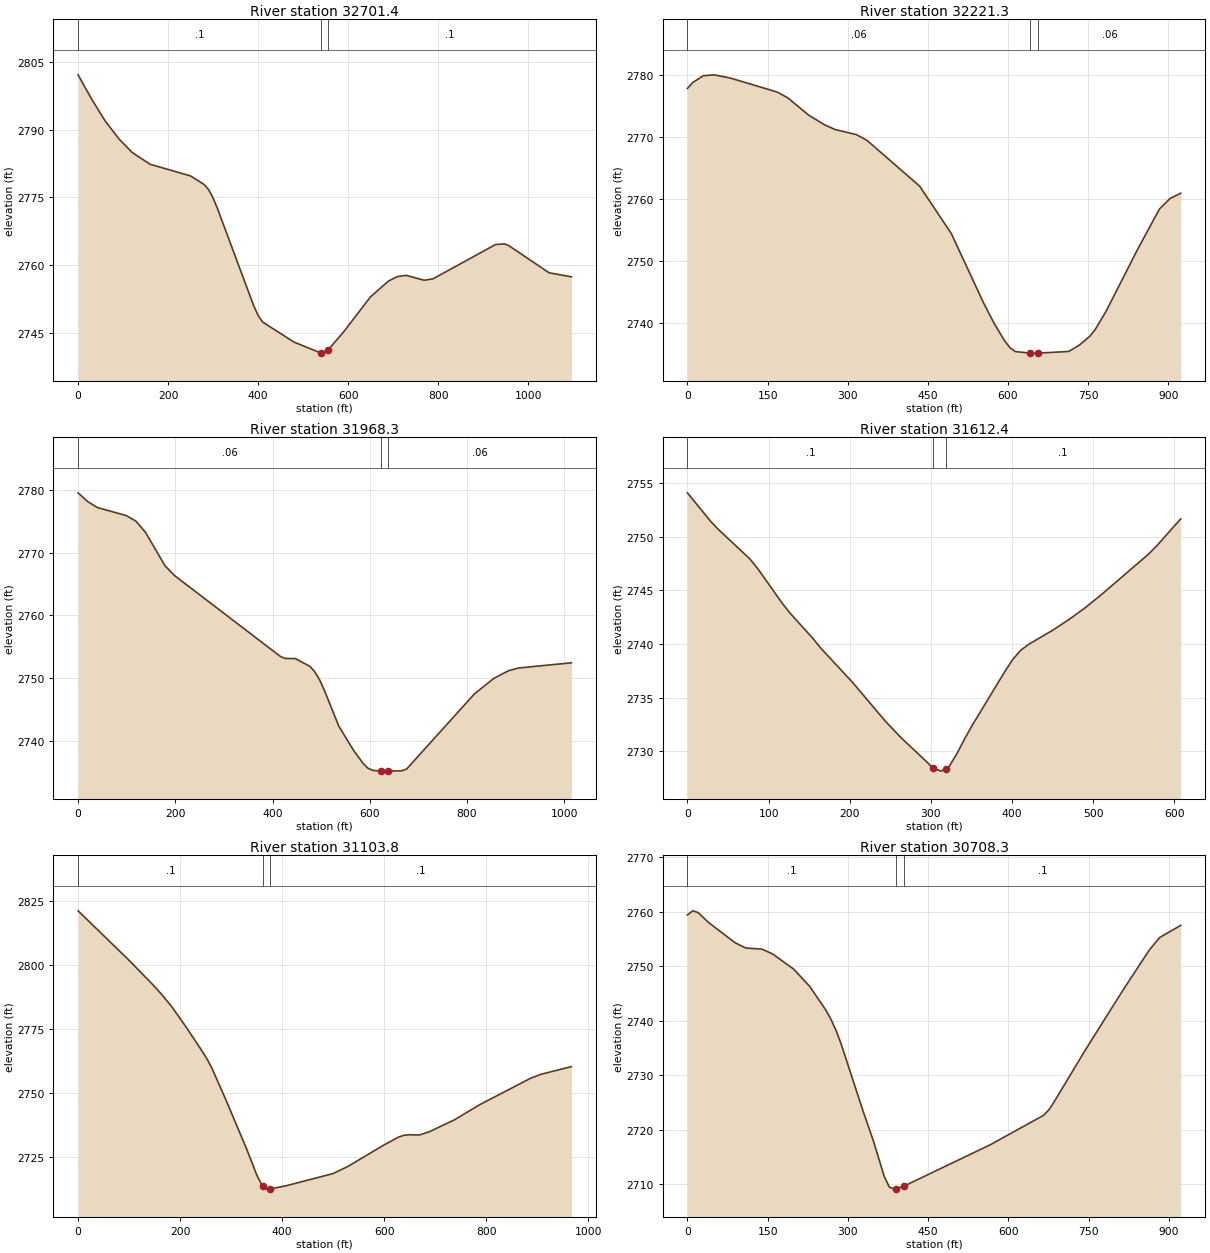
Type RM Length L Ch R = 1 ,32701.4 ,502.9,480.3,457.5
XS GIS Cut Line= 3
     2024897.163      319347.021     2025183.997      319918.886
     2025551.241      320188.932
#Sta/Elev= 30
       0 2802.16      30 2796.79      60 2791.96      90 2788.04     120 2784.95
   159.9 2782.33   249.9 2779.74   279.9 2777.84   289.9 2776.71   299.9 2774.84
   309.9 2772.42   389.9 2750.98   399.9 2748.79   409.8 2747.34   479.8 2742.89
   539.8 2740.45   539.9 2740.45   554.9 2741.12   589.8 2745.17   649.7 2752.96
   689.3 2756.42   709.1 2757.43     729 2757.69   768.6 2756.61   788.4 2756.93
   927.2 2764.53     947 2764.67   956.9 2764.26  1046.1 2758.26  1095.6 2757.37
#Mann= 3 , 0 , 0
       0      .1       0   539.9    .045       0   554.9      .1       0
Bank Sta=539.9,554.9
XS Rating Curve= 0 ,0
Exp/Cntr=0.3,0.1

Type RM Length L Ch R = 1 ,32221.3 ,249.7,252.6,255.8
XS GIS Cut Line= 3
     2024518.325      319864.766     2024927.831      320140.777
      2025357.18      320144.385
#Sta/Elev= 30
       0 2777.88     9.9 2778.84    29.6 2779.93    49.4 2780.08      79 2779.59
   167.9  2777.3   187.7 2776.37   227.2 2773.55   256.8    2772   276.6 2771.24
   316.1 2770.43   335.8 2769.51   434.6  2762.1   493.8 2754.45   553.8 2743.31
   573.7 2739.97   593.7 2737.11   603.7 2736.01   613.7 2735.38   641.2 2735.13
   656.2 2735.13   713.5  2735.4   733.5 2736.43   753.4 2737.88   763.4 2738.98
   783.4 2741.88   843.3 2752.03   883.3 2758.39   903.2 2760.11   923.2 2760.96
#Mann= 3 , 0 , 0
       0     .06       0   641.2    .045       0   656.2     .06       0
Bank Sta=641.2,656.2
XS Rating Curve= 0 ,0
Exp/Cntr=0.3,0.1

Type RM Length L Ch R = 1 ,31968.3 ,325.7,355.7,385.4
XS GIS Cut Line= 3
     2024561.532       320020.26     2024929.635       320322.98
     2025454.967      320440.447
#Sta/Elev= 30
       0  2779.6    19.9  2778.2    39.7 2777.25    99.3 2775.96   119.2 2775.07
     139 2773.25   178.7 2767.96   198.6 2766.37     417 2753.41     427 2753.13
   446.8 2753.12   476.6 2751.89   486.6 2751.05   496.5 2749.78   506.5 2748.08
   536.4 2742.32   566.3  2738.5   586.2 2736.38   596.2  2735.6   606.2 2735.25
   623.1 2735.14   626.1 2735.13   638.1 2735.13     666 2735.18     676 2735.47
   815.5 2747.48   855.4 2749.95   885.3 2751.16   905.2  2751.6  1014.9 2752.44
#Mann= 3 , 0 , 0
       0     .06       0   623.1    .045       0   638.1     .06       0
Bank Sta=623.1,638.1
XS Rating Curve= 0 ,0
Exp/Cntr=0.3,0.1

Type RM Length L Ch R = 1 ,31612.4 ,519.4,508,496.6
XS GIS Cut Line= 3
     2024861.083      320283.292     2024900.506      320432.979
     2024913.399      320885.825
#Sta/Elev= 30
       0 2754.07      29 2751.38    38.7 2750.62    77.4 2747.88    87.1 2746.96
   116.1 2743.86   125.8 2742.92   154.8 2740.49   164.6 2739.58     204 2736.37
   243.4 2732.84   263.1 2731.27     303 2728.43   312.4 2728.15     318 2728.38
   322.2 2728.56   332.1 2729.78   341.9 2731.21   351.8 2732.53   391.2 2737.44
     401 2738.57   410.8 2739.42   420.7 2739.97   450.2 2741.28   469.9 2742.26
   489.6 2743.34   509.3 2744.54   568.4 2748.38   578.3 2749.14   607.8 2751.65
#Mann= 3 , 0 , 0
       0      .1       0     303    .045       0     318      .1       0
Bank Sta=303,318
XS Rating Curve= 0 ,0
Exp/Cntr=0.3,0.1

Type RM Length L Ch R = 1 ,31103.8 ,412.5,395.4,378.4
XS GIS Cut Line= 3
     2024225.376      320191.467     2024420.909      320433.023
     2024752.844      320999.476
#Sta/Elev= 30
       0 2821.33    97.1 2802.56   145.7 2792.64   165.1 2788.38   184.5 2783.63
   213.7 2775.35   242.8 2766.61   252.5 2763.51   262.2 2759.92   291.4 2746.72
   330.7 2728.13   350.6 2717.95   360.5 2714.05   361.9 2713.84   370.5 2712.53
   376.9 2712.59   410.2 2713.96   499.8  2718.6   529.6 2721.46   599.3 2729.74
   629.1 2732.94     639 2733.59     649 2733.79   668.9 2733.68   688.8 2734.97
   738.5 2739.68   788.3 2745.63   887.7 2755.91   907.6 2757.42   967.3 2760.43
#Mann= 3 , 0 , 0
       0      .1       0   361.9    .045       0   376.9      .1       0
Bank Sta=361.9,376.9
XS Rating Curve= 0 ,0
Exp/Cntr=0.3,0.1

Type RM Length L Ch R = 1 ,30708.3 ,403.3,405.7,408.1
XS GIS Cut Line= 3
     2023835.633      320662.573     2024521.933      320864.177
      2024696.92       320974.22
#Sta/Elev= 30
       0 2759.45     9.9  2760.2    19.9 2759.89    39.7 2758.03    89.4 2754.32
   109.3 2753.36   139.1 2753.17     159 2752.29   198.7 2749.48   228.5 2746.32
   258.3 2742.02   268.2 2740.27   278.2 2738.12   288.1  2735.5   327.8 2723.54
   347.7 2717.87   367.6 2711.45   377.5 2709.41   387.4 2709.06   389.5  2709.1
   404.5  2709.6   566.3 2717.23   665.6 2722.62   675.6 2723.63   685.5 2725.12
   744.8  2734.8   813.7 2745.57     863 2752.96   882.6  2755.3     922 2757.53
#Mann= 3 , 0 , 0
       0      .1       0   389.5    .045       0   404.5      .1       0
Bank Sta=389.5,404.5
XS Rating Curve= 0 ,0
Exp/Cntr=0.3,0.1

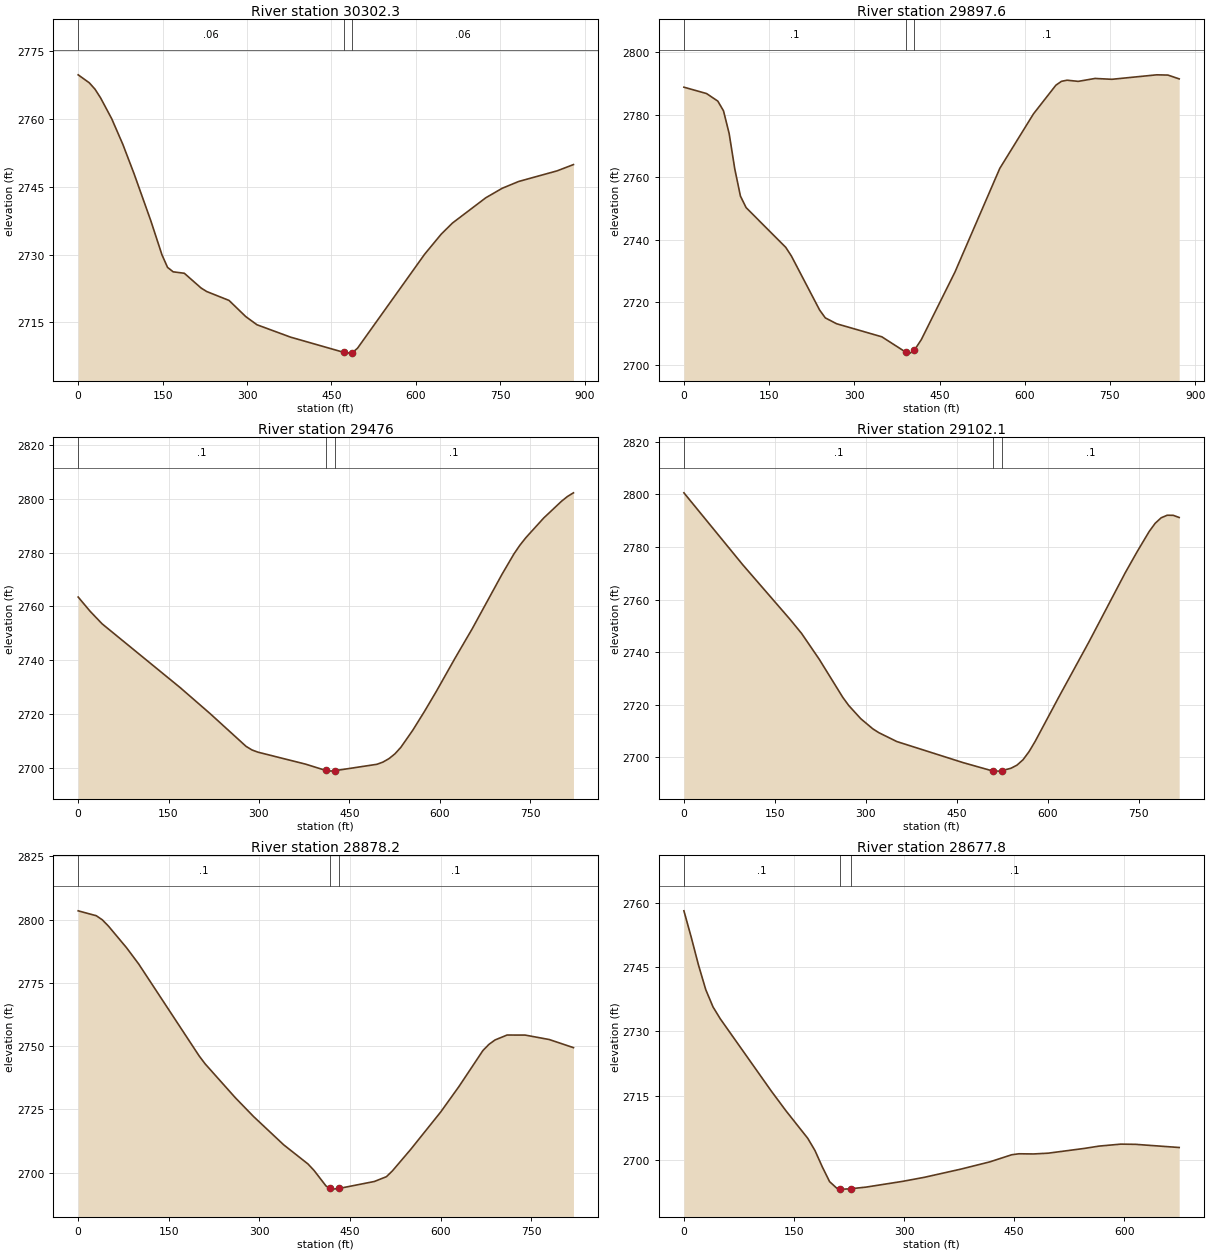
Type RM Length L Ch R = 1 ,30302.3 ,407.4,404.6,400.4
XS GIS Cut Line= 3
     2023772.559       320964.23     2024419.105      321244.819
     2024567.032      321338.626
#Sta/Elev= 30
       0 2769.73    19.8 2767.96    29.8 2766.57    39.7 2764.66    59.6 2760.02
    79.4 2754.35    99.3 2747.87     129  2737.5   148.9 2729.94   158.8 2727.17
   168.8 2726.19   188.6 2725.87   218.4 2722.61   228.3 2721.84     268 2719.87
   297.8 2716.29   317.7 2714.49   377.2 2711.76   472.2 2708.38   476.5 2708.22
   487.2 2708.33   496.3  2709.3   615.5 2730.07   645.2 2734.54   665.1 2736.98
   724.3 2742.56   753.5 2744.66   782.7 2746.16   850.8  2748.5     880 2749.89
#Mann= 3 , 0 , 0
       0     .06       0   472.2    .045       0   487.2     .06       0
Bank Sta=472.2,487.2
XS Rating Curve= 0 ,0
Exp/Cntr=0.3,0.1

Type RM Length L Ch R = 1 ,29897.6 ,427.1,421.5,417.3
XS GIS Cut Line= 3
     2023587.235      321343.029     2023970.357       321451.46
     2024433.534      321550.757
#Sta/Elev= 30
       0 2788.76    39.8 2786.73    59.7  2784.3    69.7  2781.2    79.6 2773.98
    89.6 2762.58    99.5 2753.95   109.5 2750.26   179.2 2737.58   189.1 2734.83
   238.9 2717.53   248.9 2715.02   268.8 2713.14   348.4 2708.97   390.7 2704.04
   398.2 2703.75   405.7 2704.69   417.9 2708.06   477.1 2729.64   556.1 2762.81
   615.3 2780.21   654.8 2789.39   664.6 2790.63   674.5 2790.99   694.2 2790.62
   723.8 2791.55   753.4 2791.28   832.4 2792.71   852.1 2792.63   871.9 2791.41
#Mann= 3 , 0 , 0
       0      .1       0   390.7    .045       0   405.7      .1       0
Bank Sta=390.7,405.7
XS Rating Curve= 0 ,0
Exp/Cntr=0.3,0.1

Type RM Length L Ch R = 1 ,29476   ,369.4,373.9,378.4
XS GIS Cut Line= 3
     2023617.919      321855.591     2023876.104      321836.528
     2024438.949      321849.156
#Sta/Elev= 30
       0 2763.48    19.9 2758.18    39.8 2753.53   169.3 2729.88   219.1 2720.21
   278.6  2708.1   288.5 2706.75   298.4 2705.94   377.4  2701.5   410.8 2699.17
   416.9 2698.91   425.8 2699.07   495.9 2701.45   505.8 2702.27   515.7 2703.53
   525.6 2705.31   535.4 2707.72   555.2 2714.06     575 2721.18   594.7 2728.63
   624.3 2740.37     654 2751.75   703.4 2771.95   723.1 2779.46     733  2782.7
   742.9  2785.5   772.5 2792.79   802.1 2799.02     812 2800.79   821.9 2802.14
#Mann= 3 , 0 , 0
       0      .1       0   410.8    .045       0   425.8      .1       0
Bank Sta=410.8,425.8
XS Rating Curve= 0 ,0
Exp/Cntr=0.3,0.1

Type RM Length L Ch R = 1 ,29102.1 ,227.6,223.2,218.3
XS GIS Cut Line= 3
     2023493.658      322110.734     2023751.629      322155.834
     2024292.826      322276.702
#Sta/Elev= 30
       0 2800.62      97 2773.23   174.6 2752.54     194 2747.08   223.1 2737.24
   261.9 2722.75   271.8 2719.62   291.6  2714.6   311.4 2710.76   321.3  2709.3
     351 2705.92   459.9 2697.92   509.4 2694.69   519.3 2694.66   524.4 2694.86
   539.2 2695.76     549 2696.94     559 2698.99   568.9 2702.08   578.8 2705.91
   618.4 2723.04   667.9 2743.97   727.3 2770.11   747.1 2778.21   766.9 2785.88
   776.8 2789.01   786.7 2791.12   796.6 2792.08   806.5 2792.06   816.4 2791.23
#Mann= 3 , 0 , 0
       0      .1       0   509.4    .045       0   524.4      .1       0
Bank Sta=509.4,524.4
XS Rating Curve= 0 ,0
Exp/Cntr=0.3,0.1

Type RM Length L Ch R = 1 ,28878.2 ,200.6,200.3,200.4
XS GIS Cut Line= 3
     2023481.274      322358.154     2023890.915      322382.497
     2024300.274      322389.698
#Sta/Elev= 30
       0 2803.52      30 2801.58      40 2799.95      50 2797.51    80.1 2788.92
   100.1 2782.53   200.2 2746.18   210.2 2743.01   260.2 2729.62   290.3 2722.21
   340.3    2711   380.3 2703.47   390.4  2700.9   410.4 2694.71   416.6 2693.97
   420.4 2693.51   431.6 2693.77   490.2 2696.53   510.2 2698.42   520.2 2700.74
   550.2 2709.15   600.1 2724.02     630 2733.97     670 2748.31     680 2750.75
     690 2752.47   709.9 2754.42   739.9  2754.4   779.8 2752.64   819.8 2749.44
#Mann= 3 , 0 , 0
       0      .1       0   416.6    .045       0   431.6      .1       0
Bank Sta=416.6,431.6
XS Rating Curve= 0 ,0
Exp/Cntr=0.3,0.1

Type RM Length L Ch R = 1 ,28677.8 ,369.9,375.5,381.1
XS GIS Cut Line= 2
     2023675.861      322577.968     2024350.554        322592.4
#Sta/Elev= 30
       0 2758.23     9.9  2752.1    19.8 2745.58    29.8 2739.77    39.7 2735.73
    49.6 2732.95   119.1 2716.05   138.9 2711.47   168.7 2705.01   178.6 2702.13
   188.6  2698.3   198.5 2694.86   208.4 2693.31   212.2 2693.23   218.3 2693.11
   227.2  2693.2   248.1 2693.58   297.7 2694.92   327.5 2695.87   377.1 2697.78
   416.8 2699.49   446.6 2701.15   456.5 2701.38   476.4 2701.34   496.2 2701.52
   545.8 2702.64   565.7 2703.18   595.4 2703.64   615.3 2703.59   674.8 2702.85
#Mann= 3 , 0 , 0
       0      .1       0   212.2    .045       0   227.2      .1       0
Bank Sta=212.2,227.2
XS Rating Curve= 0 ,0
Exp/Cntr=0.3,0.1

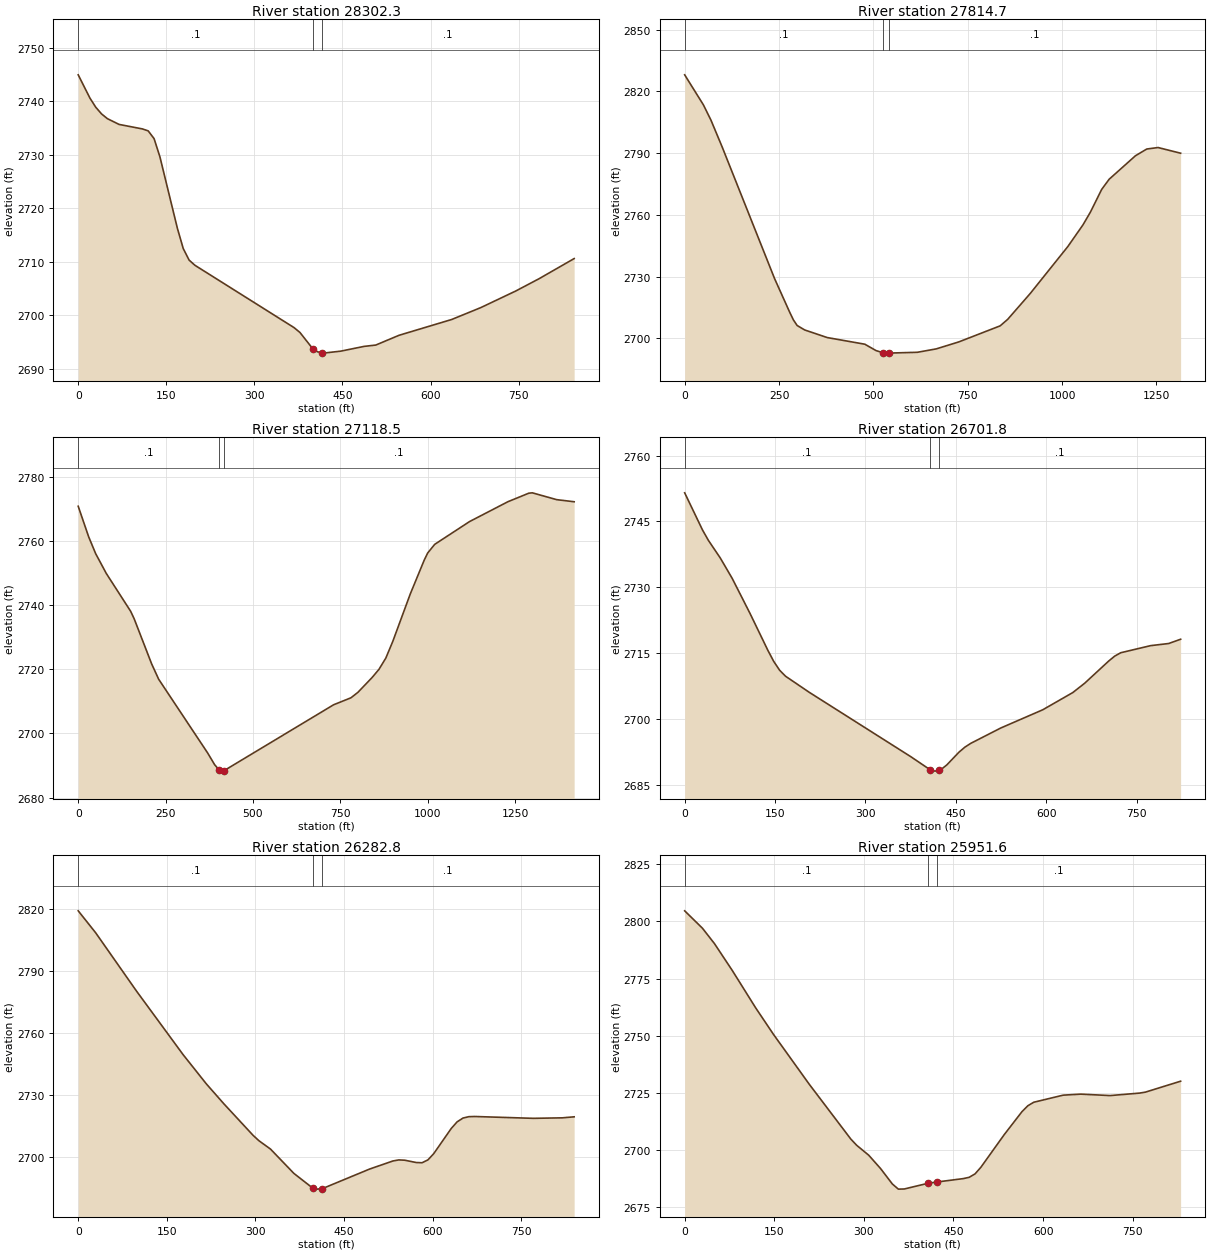
Type RM Length L Ch R = 1 ,28302.3 ,464,487.3,478.8
XS GIS Cut Line= 2
     2023453.537      322845.611      2024267.57      323070.457
#Sta/Elev= 30
       0 2744.97    19.9 2740.63    29.8 2738.92    39.7 2737.66    49.7 2736.77
    69.6 2735.69   109.3 2734.85   119.2 2734.48   129.2 2733.03   139.1 2729.64
   168.9 2716.25   178.8 2712.48   188.8 2710.31   198.7 2709.34   367.6 2697.67
   377.6 2696.76   397.4    2694   400.3 2693.75   407.4 2693.15   415.3 2692.95
   417.3  2692.9   447.1 2693.27   486.8 2694.16   506.7 2694.41   546.4 2696.24
   635.9 2699.19   685.6 2701.42   745.2 2704.53   784.9 2706.83   844.5 2710.59
#Mann= 3 , 0 , 0
       0      .1       0   400.3    .045       0   415.3      .1       0
Bank Sta=400.3,415.3
XS Rating Curve= 0 ,0
Exp/Cntr=0.3,0.1

Type RM Length L Ch R = 1 ,27814.7 ,684,695.7,717.4
XS GIS Cut Line= 3
     2023239.295      323157.049     2023439.538      323214.777
     2024484.049      323577.379
#Sta/Elev= 30
       0 2828.01    49.6 2813.43    69.5 2806.06    99.2 2793.05   238.3 2729.03
   278.1 2712.81   288.1 2709.01     298  2706.3     318 2704.13   377.7 2700.44
   477.3 2697.21   507.2  2694.1   526.8 2692.98   537.1 2692.88   541.8  2692.9
   616.8 2693.29   666.6 2694.94   726.4 2698.33   835.9 2706.12   855.9 2709.28
   915.6 2721.83  1015.2 2744.62  1055.1 2755.08    1075 2761.32  1104.9 2772.36
  1124.8 2777.32  1194.5 2788.72  1224.4 2791.98  1254.3 2792.71  1314.1 2789.95
#Mann= 3 , 0 , 0
       0      .1       0   526.8    .045       0   541.8      .1       0
Bank Sta=526.8,541.8
XS Rating Curve= 0 ,0
Exp/Cntr=0.3,0.1

Type RM Length L Ch R = 1 ,27118.5 ,419.6,416.6,413.6
XS GIS Cut Line= 3
     2023075.219      323545.089     2023621.741       324030.18
     2024307.258      324095.124
#Sta/Elev= 30
       0 2770.77      30 2761.23      50    2756    80.1 2749.89   150.2 2738.04
   160.2 2735.71   210.2 2721.67   230.2 2716.91   370.4 2693.94   390.4 2690.29
   402.6 2688.72   410.4 2688.28   417.6 2688.44   730.8 2708.94   780.6 2711.12
   800.6 2712.83   840.5 2717.37   860.5 2719.94   880.4  2723.5   900.4 2728.72
   950.3 2743.45   990.2 2753.98  1000.2 2756.22  1020.2  2758.9    1120    2766
  1229.7 2772.18  1289.6 2774.84  1299.6 2774.95  1369.4 2772.82  1419.3 2772.17
#Mann= 3 , 0 , 0
       0      .1       0   402.6    .045       0   417.6      .1       0
Bank Sta=402.6,417.6
XS Rating Curve= 0 ,0
Exp/Cntr=0.3,0.1

Type RM Length L Ch R = 1 ,26701.8 ,431.7,418.9,406.2
XS GIS Cut Line= 3
     2022857.915      323904.381     2023058.896       324093.32
     2023512.983      324398.672
#Sta/Elev= 30
       0 2751.52    29.6 2743.07    39.4  2740.7    59.1  2736.7    78.8 2732.08
   108.4  2724.1   137.9 2715.75   147.8 2713.18   157.6 2711.17   167.5  2709.8
   206.9 2706.14   375.3 2691.51   406.7  2688.6   415.1 2688.23   421.7 2688.45
   425.1 2688.56     435 2689.64   454.9  2692.5   464.9 2693.67   474.8 2694.55
   524.6 2698.04   594.2 2702.18     644 2706.09   663.9 2708.23   703.7 2713.27
   713.6 2714.38   723.6 2715.15   773.3 2716.77   803.2 2717.25     823 2718.22
#Mann= 3 , 0 , 0
       0      .1       0   406.7    .045       0   421.7      .1       0
Bank Sta=406.7,421.7
XS Rating Curve= 0 ,0
Exp/Cntr=0.3,0.1

Type RM Length L Ch R = 1 ,26282.8 ,322.3,331.1,339.8
XS GIS Cut Line= 3
     2022560.221      324481.922     2023181.568       324504.63
     2023386.657      324578.755
#Sta/Elev= 30
       0 2819.35    29.6 2808.69    98.7 2780.44   177.6 2749.62   217.1 2735.39
   246.7 2725.76   296.1 2710.49     306 2707.88   325.7  2703.8   365.2 2692.03
   394.8 2685.42   398.3 2685.06   404.6  2684.4   413.3 2684.63   493.5 2694.14
   532.9 2698.05   542.8 2698.56   552.7 2698.43   572.4  2697.3   582.3 2697.19
   592.2 2698.58     602  2701.6   631.7 2713.81   641.6 2717.01   651.5 2718.85
   661.4 2719.53   671.3 2719.62   770.4 2718.73     820 2718.97   839.8 2719.46
#Mann= 3 , 0 , 0
       0      .1       0   398.3    .045       0   413.3      .1       0
Bank Sta=398.3,413.3
XS Rating Curve= 0 ,0
Exp/Cntr=0.3,0.1

Type RM Length L Ch R = 1 ,25951.6 ,334.6,331.3,326.7
XS GIS Cut Line= 3
     2022558.494      324625.844     2022925.508      324802.557
     2023307.572      324983.724
#Sta/Elev= 30
       0 2804.58    29.8 2796.96    49.7 2790.31    79.5 2778.59   119.2 2762.04
     149 2750.46   208.6 2728.78   278.2 2704.82   288.1 2702.09     308 2697.82
   327.9 2691.97   347.7  2685.2   357.7 2682.97   367.6 2683.03   407.3 2685.52
   422.3 2686.09   466.3 2687.56   476.2 2688.13     486 2689.61   495.8 2692.51
   535.2 2706.88   564.7 2716.84   574.5 2719.41   584.3 2720.93   633.5 2724.03
     663 2724.48   712.2 2723.85   761.4 2724.93   771.2 2725.35   830.2 2730.13
#Mann= 3 , 0 , 0
       0      .1       0   407.3    .045       0   422.3      .1       0
Bank Sta=407.3,422.3
XS Rating Curve= 0 ,0
Exp/Cntr=0.3,0.1

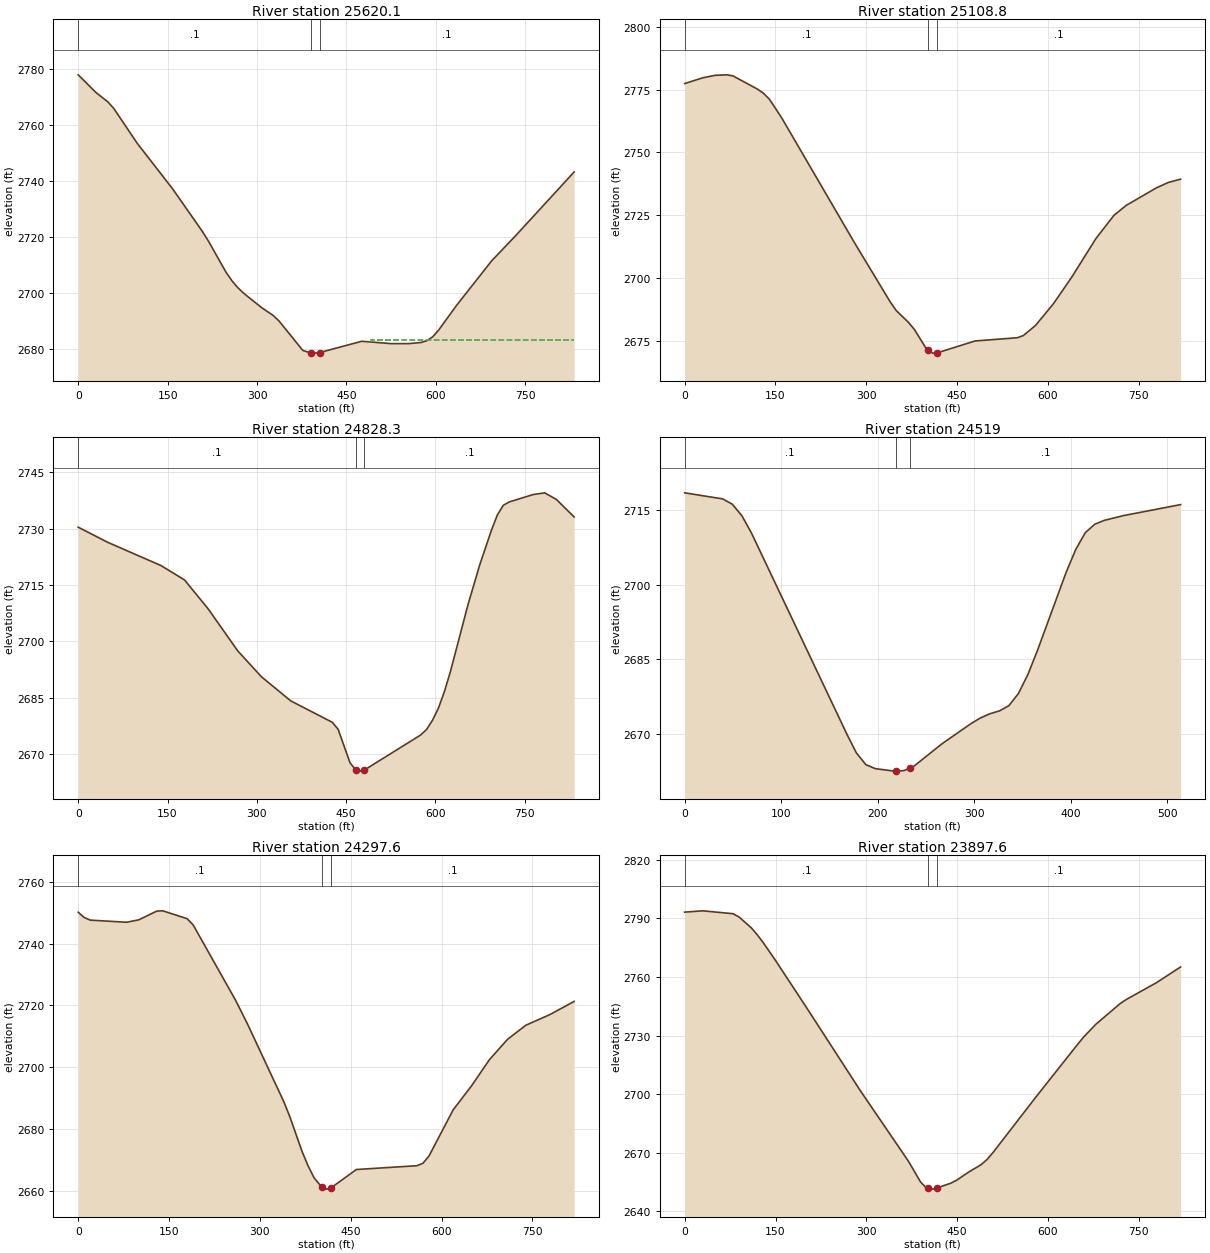
Type RM Length L Ch R = 1 ,25620.1 ,508.3,511.3,515.7
XS GIS Cut Line= 3
     2022421.477      324947.152      2023015.15      325171.205
     2023165.259      325299.862
#Sta/Elev= 30
       0 2778.07    29.7 2771.76    49.6 2768.43    59.5  2766.1    99.2 2753.53
   158.6 2737.24   208.2  2722.1   218.1 2718.76   247.9 2707.52   257.8 2704.46
   267.7 2701.97   277.6 2699.96   307.4 2694.86   327.2    2692   337.1    2690
   376.8 2679.52   389.9 2678.56   396.6 2678.53   404.9 2678.72   475.9 2682.77
   525.5 2681.92   555.2 2681.94   575.1 2682.33     585 2682.96   594.9 2684.37
   604.8 2686.76   634.5 2695.49   693.8 2711.55   733.4 2720.39   832.2 2743.34
#Mann= 3 , 0 , 0
       0      .1       0   389.9    .045       0   404.9      .1       0
#XS Ineff= 2 , 0
                           491.9         2683.24
Permanent Ineff=
       F       F
Bank Sta=389.9,404.9
XS Rating Curve= 0 ,0
Exp/Cntr=0.3,0.1

Type RM Length L Ch R = 1 ,25108.8 ,280.6,280.5,280.5
XS GIS Cut Line= 2
     2022216.183      325388.264     2022968.302      325713.189
#Sta/Elev= 30
       0 2777.44      30 2779.74      50 2780.71    69.9 2780.92    79.9 2780.48
   119.9 2775.27   129.9 2773.63   139.9 2771.23   159.9 2763.93   279.8 2714.32
   339.7 2690.38   349.7 2686.94   369.7  2682.3   379.7 2679.41   399.7 2671.57
   402.3 2671.17   409.6 2670.04   417.3 2670.16   479.6 2674.88   549.5 2676.17
   559.5 2677.04   579.5 2681.04   609.5 2689.82   639.5 2700.34   679.4  2715.7
   709.4 2725.01   729.4  2728.9   779.3 2735.88   799.3 2738.07   819.3 2739.35
#Mann= 3 , 0 , 0
       0      .1       0   402.3    .045       0   417.3      .1       0
Bank Sta=402.3,417.3
XS Rating Curve= 0 ,0
Exp/Cntr=0.3,0.1

Type RM Length L Ch R = 1 ,24828.3 ,323.5,309.3,295.1
XS GIS Cut Line= 3
     2022003.255      325700.785     2022403.597      325773.286
     2022794.955      325941.678
#Sta/Elev= 30
       0 2730.37    49.6 2726.34   138.9 2720.16   178.6 2716.32   218.3 2708.61
   267.9 2697.44   307.6 2690.55   357.2 2684.09   426.7 2678.42   436.6 2676.53
   456.4 2667.65   465.8 2665.77   476.2 2665.41   480.8 2665.72   575.3 2675.05
   585.2 2676.52   595.1 2678.98     605  2682.2   614.9 2686.55   624.8 2691.74
   654.6 2709.72   674.4 2720.37   694.2 2729.65   704.1 2733.68     714 2736.21
   723.9 2737.09   763.6 2739.04   783.4 2739.52   803.2 2737.74   832.9 2733.09
#Mann= 3 , 0 , 0
       0      .1       0   465.8    .045       0   480.8      .1       0
Bank Sta=465.8,480.8
XS Rating Curve= 0 ,0
Exp/Cntr=0.3,0.1

Type RM Length L Ch R = 1 ,24519   ,210.9,221.3,231.8
XS GIS Cut Line= 2
     2022150.587      326127.771     2022652.547      326018.178
#Sta/Elev= 30
       0  2718.4    39.5 2717.18    49.4 2716.11    59.3  2713.8    69.2 2710.34
     168 2670.05   177.8  2666.3   187.7 2663.92   197.6 2663.11   217.4 2662.62
   218.7 2662.63   227.2 2662.72   233.7 2663.26   237.1 2663.55   266.8 2668.13
   296.4 2672.11   306.3 2673.27   316.2 2674.12   326.1 2674.69   335.9 2675.75
   345.8 2678.18   355.7 2682.04   365.6 2686.87   395.2 2702.46   405.1 2707.02
     415 2710.41   424.9 2712.11   434.7 2712.88   454.5 2713.83   513.8 2716.04
#Mann= 3 , 0 , 0
       0      .1       0   218.7    .045       0   233.7      .1       0
Bank Sta=218.7,233.7
XS Rating Curve= 0 ,0
Exp/Cntr=0.3,0.1

Type RM Length L Ch R = 1 ,24297.6 ,393,400,406.9
XS GIS Cut Line= 3
     2021948.277      326200.985     2022345.908      326298.864
     2022743.538      326396.742
#Sta/Elev= 30
       0 2750.13      10  2748.4      20 2747.57    79.9 2746.88    99.9 2747.66
   129.8 2750.49   139.8 2750.58   179.8 2748.04   189.8 2746.03   259.7  2721.7
   279.7  2713.9   339.6 2688.77   349.6 2683.88   369.6 2672.73   379.5 2668.08
   389.5 2664.17     402 2661.18   409.5  2660.5     417 2660.84   459.4 2666.85
   559.3 2668.08   569.3 2668.87   579.3 2671.22   619.2 2686.16   649.2 2693.83
   679.2 2702.43   709.1 2709.01   739.1 2713.53     779    2717     819 2721.26
#Mann= 3 , 0 , 0
       0      .1       0     402    .045       0     417      .1       0
Bank Sta=402,417
XS Rating Curve= 0 ,0
Exp/Cntr=0.3,0.1

Type RM Length L Ch R = 1 ,23897.6 ,399.9,400,400.1
XS GIS Cut Line= 3
      2021836.43      326447.505     2022185.355      326661.845
     2022534.281      326876.184
#Sta/Elev= 30
       0 2793.17      30 2793.83    79.9 2792.36    89.9 2790.64   109.9 2785.17
   119.8 2781.61   129.8  2777.5   149.8 2768.54   199.8 2744.99   289.6 2702.02
   369.6 2665.66   389.5  2655.1   399.5 2651.92     402 2651.79   409.5 2651.41
     417 2652.02   439.5 2654.46   449.4 2656.04   469.4 2660.22   489.4  2663.9
   499.4 2666.59   509.4 2670.22   579.3 2698.26   649.2  2725.6   659.2 2729.37
   679.2 2735.83   719.1 2746.35   729.1 2748.42     779 2757.03     819 2765.13
#Mann= 3 , 0 , 0
       0      .1       0     402    .045       0     417      .1       0
Bank Sta=402,417
XS Rating Curve= 0 ,0
Exp/Cntr=0.3,0.1