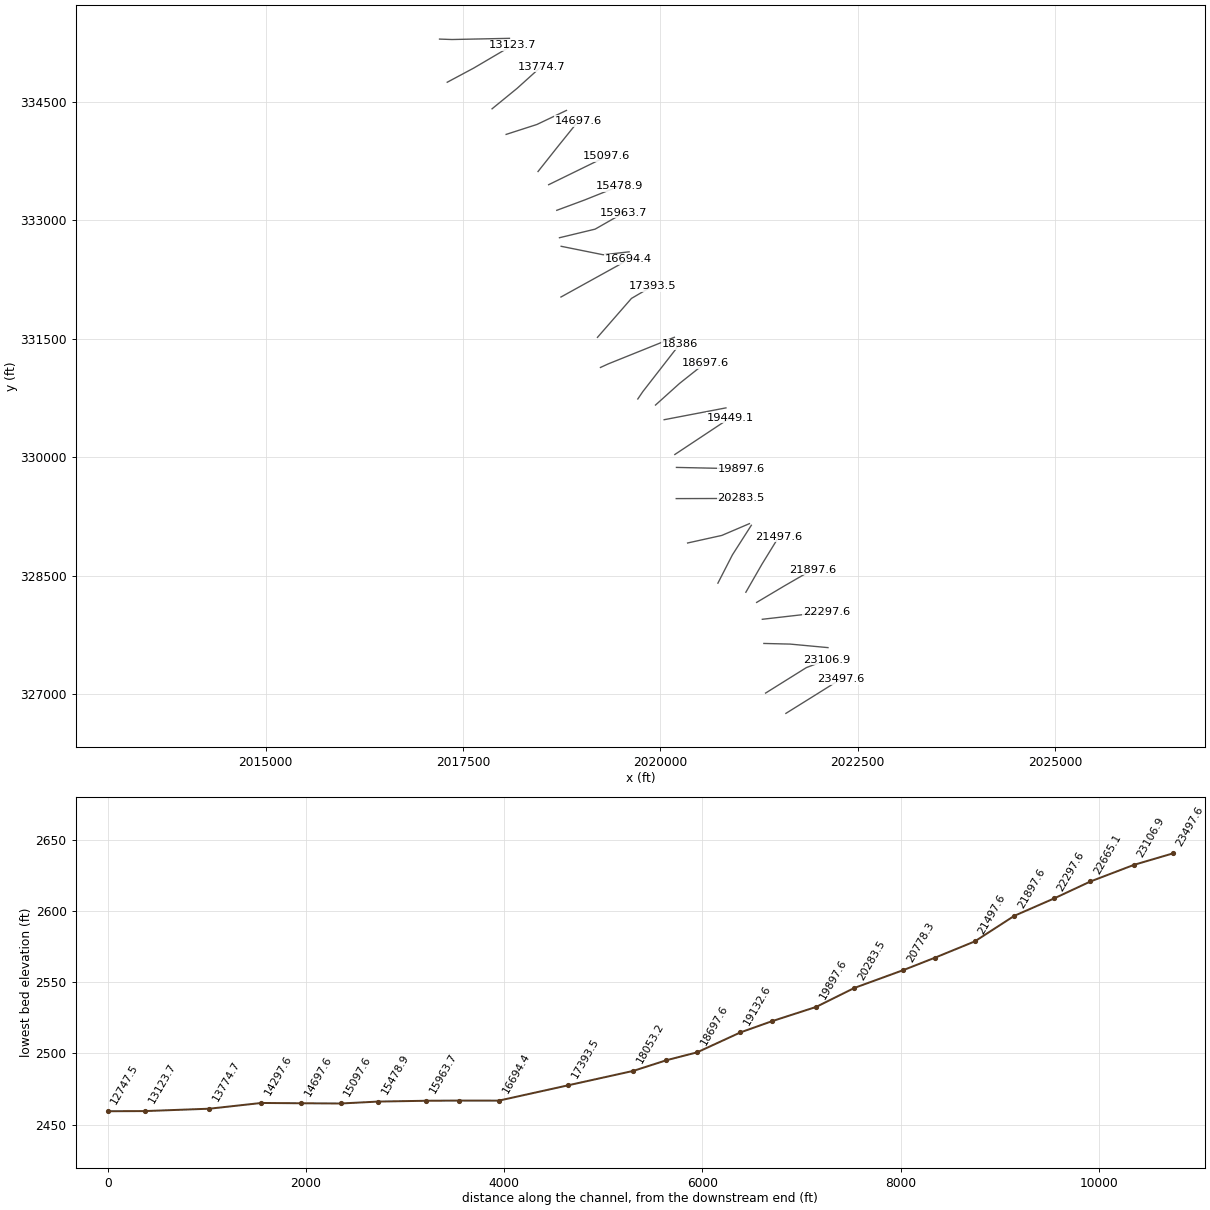
HEC-RAS study SewellCrk.prj: SewellCrk

--- SewellCrk.g01 (geometry) --- (continued)

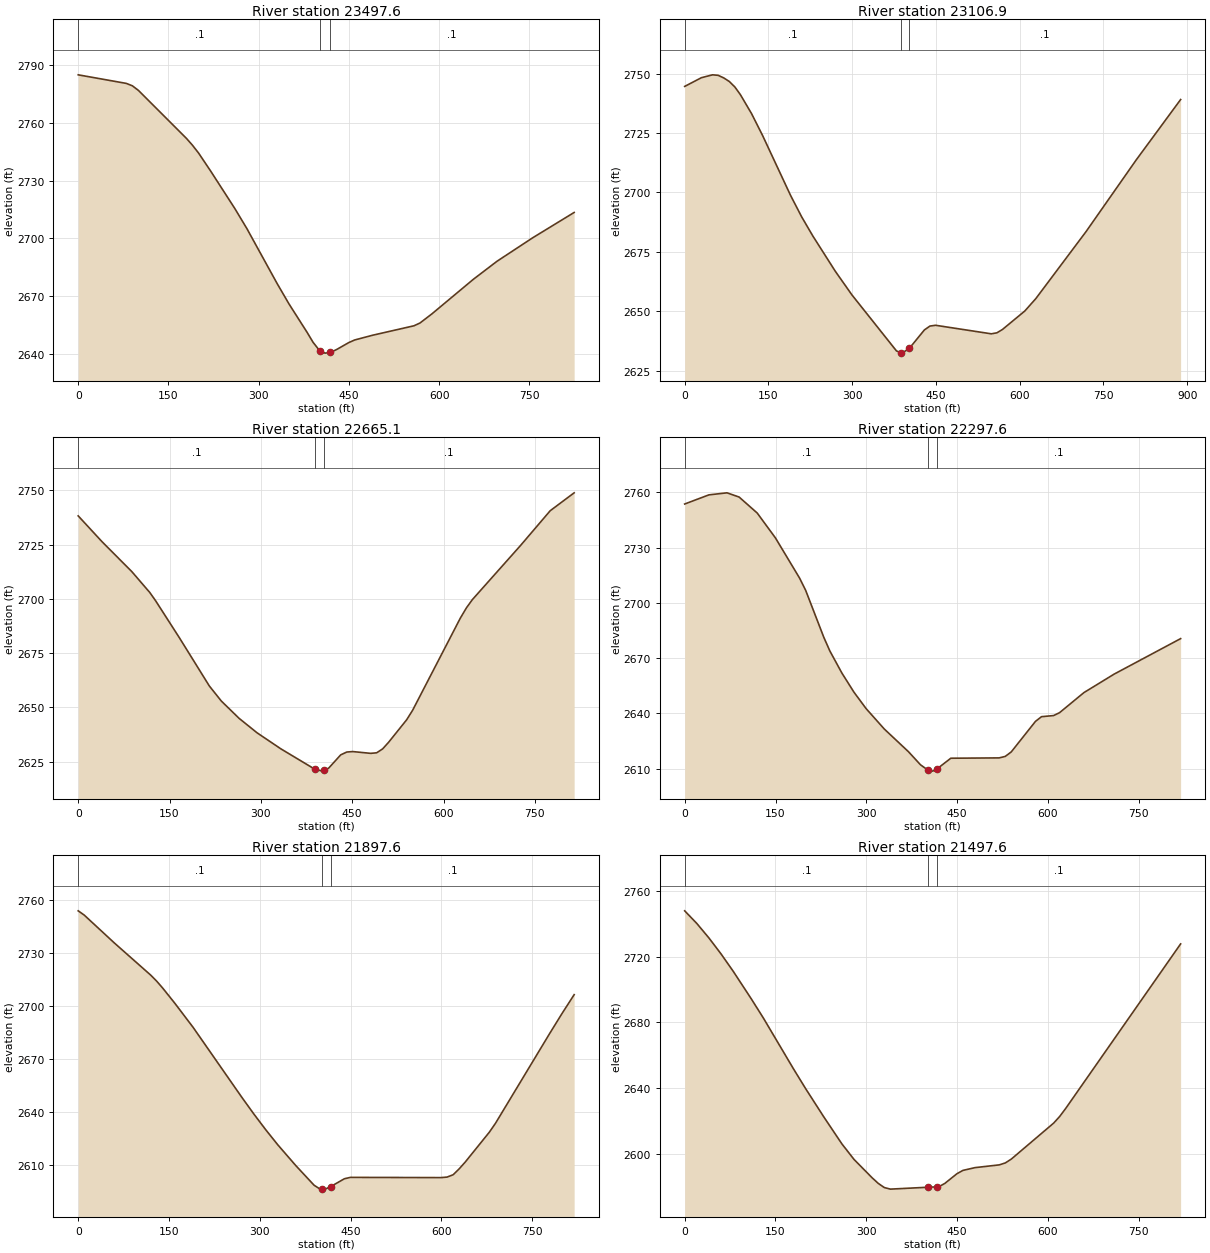
Type RM Length L Ch R = 1 ,23497.6 ,390.6,390.7,390.8
XS GIS Cut Line= 3
      2021590.84      326757.684     2021939.086      326974.539
     2022290.281      327193.891
#Sta/Elev= 30
       0 2784.96      80  2780.5      90 2779.26   100.1 2776.86   180.1 2751.86
   190.1  2748.3   200.1 2744.29   220.1 2734.97   260.2 2715.53   280.2 2705.14
   330.2 2676.73   350.2 2665.97   380.2 2651.25   390.2 2646.03   400.2 2642.02
   402.7  2641.6   410.2 2640.33   417.7 2640.68   420.1 2640.79     430 2642.29
   449.7 2645.81   459.5 2647.16   489.1 2649.61   558.1 2654.54     568 2655.97
   587.7 2660.68   656.7 2678.68   696.2 2688.09   755.3 2700.25   824.3 2713.43
#Mann= 3 , 0 , 0
       0      .1       0   402.7    .045       0   417.7      .1       0
Bank Sta=402.7,417.7
XS Rating Curve= 0 ,0
Exp/Cntr=0.3,0.1

Type RM Length L Ch R = 1 ,23106.9 ,456.6,441.7,426.9
XS GIS Cut Line= 3
     2021333.605      327014.717     2021850.223      327337.346
     2022111.422      327435.956
#Sta/Elev= 30
       0 2744.66      30 2748.33    49.9 2749.54    59.9 2749.33    69.9 2748.25
    79.9 2746.74    89.9 2744.42    99.8 2741.19   119.8  2733.2   139.8 2723.87
   189.7 2698.75   209.7 2689.67   229.6 2681.66   269.6 2666.89   299.6 2656.86
   379.4 2633.27   387.5 2632.52   389.4 2632.35   402.5 2634.38   429.4 2642.13
   439.3 2643.74   449.3 2644.08   549.2 2640.48   559.2  2640.9   569.1 2642.29
   609.1 2650.06     629 2655.32   718.8 2683.48   808.5 2713.62   888.3 2739.13
#Mann= 3 , 0 , 0
       0      .1       0   387.5    .045       0   402.5      .1       0
Bank Sta=387.5,402.5
XS Rating Curve= 0 ,0
Exp/Cntr=0.3,0.1

Type RM Length L Ch R = 1 ,22665.1 ,362.8,367.4,372.1
XS GIS Cut Line= 3
     2021311.731      327643.123     2021644.568      327635.005
      2022124.18      327590.341
#Sta/Elev= 30
       0 2738.22    39.2  2726.3    88.1 2712.53   117.5 2702.95   127.3 2699.05
   166.5 2681.93   215.4 2659.85     235 2652.94   264.4 2644.91   293.8 2638.28
   332.9 2630.89     389 2621.45   401.8 2620.63     404 2620.95   411.6 2622.07
   431.2 2628.13   441.1 2629.42   450.9 2629.64   480.4 2628.82   490.2 2629.07
     500 2630.86   509.9 2633.94   539.4 2644.25   549.2 2648.62   627.8 2691.19
   637.7 2695.86   647.5 2699.67   726.2 2724.47   775.3  2740.6   814.6 2748.84
#Mann= 3 , 0 , 0
       0      .1       0     389    .045       0     404      .1       0
Bank Sta=389,404
XS Rating Curve= 0 ,0
Exp/Cntr=0.3,0.1

Type RM Length L Ch R = 1 ,22297.6 ,390.4,400,409.2
XS GIS Cut Line= 3
     2021292.301      327949.242     2021699.153      327995.739
     2022106.005      328042.235
#Sta/Elev= 30
       0 2753.64      40  2758.6    69.9 2759.71    89.9 2757.42   119.8 2748.74
   149.8 2735.29   189.8 2713.42   199.8  2706.8   229.7 2681.37   239.7 2673.94
   259.7 2661.88   279.7 2651.48   299.6 2642.64   329.6 2631.57   369.6 2619.24
   389.5 2612.13     402  2609.2   409.5 2608.71     417 2609.99   439.5 2615.71
   519.4 2615.89   529.4  2616.7   539.3 2619.13   579.3  2635.7   589.3 2638.25
   609.3 2638.86   619.2 2640.45   659.2 2651.29   709.1 2661.32     819  2680.6
#Mann= 3 , 0 , 0
       0      .1       0     402    .045       0     417      .1       0
Bank Sta=402,417
XS Rating Curve= 0 ,0
Exp/Cntr=0.3,0.1

Type RM Length L Ch R = 1 ,21897.6 ,388.4,400,411.2
XS GIS Cut Line= 3
     2021220.224      328162.823     2021572.277      328372.155
     2021926.836      328577.011
#Sta/Elev= 30
       0 2754.05      10 2751.62    59.9  2735.8   119.9 2717.62   129.9 2714.14
   139.9 2710.18   159.8 2701.65   189.8 2688.09   269.7 2648.78   289.7 2639.25
   309.7 2630.18   329.7 2621.61   359.6  2609.8   389.6 2598.76   399.6 2596.56
   402.1 2596.62   409.6 2596.81   417.1 2598.02   439.6 2602.42   449.5 2603.21
   599.4 2603.08   609.3 2603.38   619.3 2604.71   629.3 2608.07   639.3 2611.92
   679.2 2628.86   689.2 2633.82   779.1 2684.87   799.1 2695.96   819.1  2706.6
#Mann= 3 , 0 , 0
       0      .1       0   402.1    .045       0   417.1      .1       0
Bank Sta=402.1,417.1
XS Rating Curve= 0 ,0
Exp/Cntr=0.3,0.1

Type RM Length L Ch R = 1 ,21497.6 ,398.9,399.8,399.4
XS GIS Cut Line= 3
     2021083.449       328291.53     2021287.562      328646.795
     2021502.159      328995.515
#Sta/Elev= 30
       0  2747.9      20 2740.24      40 2731.42      60 2721.72      80 2711.21
   109.9 2694.42   129.9 2682.73   179.9 2651.66   199.9 2639.67   229.8 2622.54
   259.8 2606.06   279.8 2596.63   309.8 2585.43   319.8 2582.07   329.8 2579.54
   339.8 2578.59   402.2 2579.75   417.2 2579.94   419.7 2580.03   429.7 2582.06
   449.7 2587.96   459.7 2589.99   479.6 2591.67   519.6 2593.34   529.6 2594.52
   539.6 2596.88   609.5 2618.76   619.4 2622.77   629.4 2627.69   819.2 2727.77
#Mann= 3 , 0 , 0
       0      .1       0   402.2    .045       0   417.2      .1       0
Bank Sta=402.2,417.2
XS Rating Curve= 0 ,0
Exp/Cntr=0.3,0.1

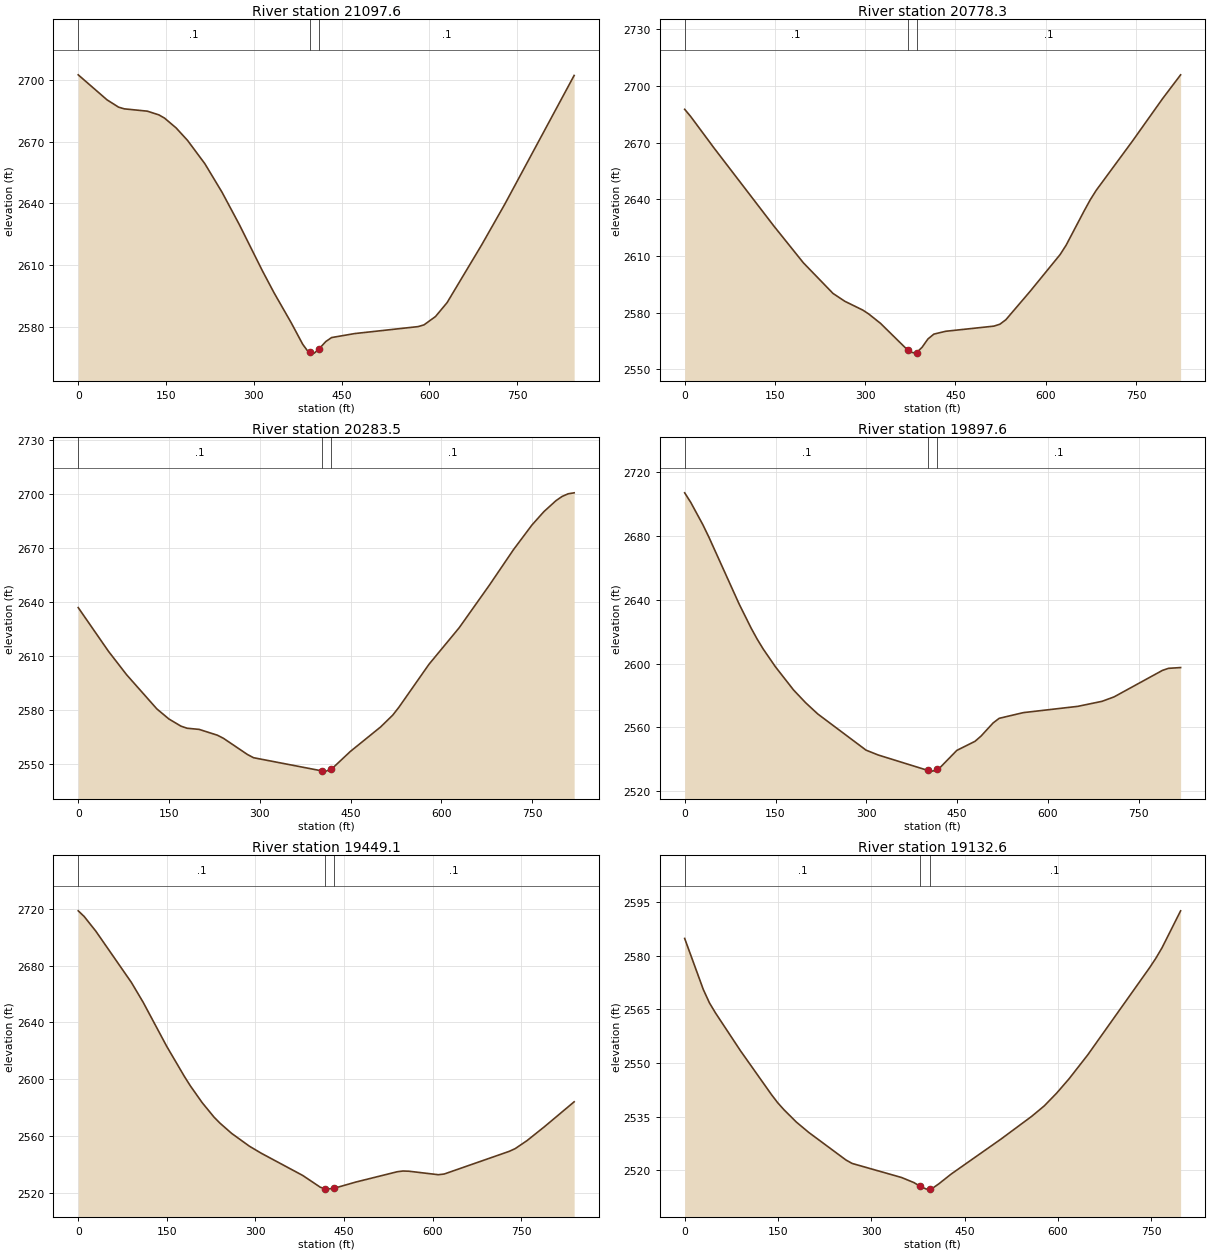
Type RM Length L Ch R = 1 ,21097.6 ,339.2,319.4,301.7
XS GIS Cut Line= 3
      2020729.15      328406.484     2020913.425      328765.336
     2021152.803      329139.357
#Sta/Elev= 30
       0 2702.54    49.2 2690.39    68.9 2686.83    78.7    2686   118.1 2684.87
   137.8 2683.07   147.6 2681.48   167.3 2676.73   186.9 2670.63   216.5 2659.29
     246 2645.34   275.5 2629.63   314.8 2607.23   334.5 2596.64     364 2581.98
   383.7  2571.5   393.6 2567.67   395.9 2567.56   403.4 2567.22   410.9 2569.08
   423.1 2572.85     433 2574.79   472.5 2576.73     581 2580.12   590.9 2580.96
   610.6 2585.02   630.4 2591.79   689.6 2619.92     729 2639.65   847.5 2702.24
#Mann= 3 , 0 , 0
       0      .1       0   395.9    .045       0   410.9      .1       0
Bank Sta=395.9,410.9
XS Rating Curve= 0 ,0
Exp/Cntr=0.3,0.1

Type RM Length L Ch R = 1 ,20778.3 ,499.7,494.8,489.9
XS GIS Cut Line= 3
     2020345.438      328915.203     2020778.669      329010.986
     2021128.601       329160.11
#Sta/Elev= 30
       0 2687.59     9.9 2683.82    49.3 2666.89   147.9 2625.92   197.2 2606.34
   246.5 2590.11   266.2 2585.94   295.8 2581.33   305.7 2579.27   325.4 2574.28
   370.4 2560.19   374.7 2559.07   384.5 2558.51   385.4 2558.79   394.4 2561.56
   404.2    2566   414.1 2568.58   433.8 2570.08   513.8  2572.8   523.8 2573.82
   533.8 2576.22   573.8 2591.14   623.9  2610.7   633.9 2615.69   663.9 2633.87
   673.9 2639.67   683.9 2644.72     744 2670.74     794 2693.18   824.1 2705.85
#Mann= 3 , 0 , 0
       0      .1       0   370.4    .045       0   385.4      .1       0
Bank Sta=370.4,385.4
XS Rating Curve= 0 ,0
Exp/Cntr=0.3,0.1

Type RM Length L Ch R = 1 ,20283.5 ,386.4,385.8,385.3
XS GIS Cut Line= 2
     2020201.345      329477.311     2021020.847      329479.196
#Sta/Elev= 30
       0 2636.91      50 2612.61      80 2599.56   129.9 2580.59   149.9 2574.96
   169.9 2570.97   179.9 2569.83   199.9 2569.18   229.9 2565.96   239.9 2564.25
   279.8 2555.19   289.8 2553.43   402.1 2546.15   409.8 2545.98   417.1 2547.08
   419.8 2547.48   449.7 2556.92   499.7 2570.54   519.7  2577.1   529.7 2581.39
   579.6 2605.37   629.6 2625.72   679.6 2649.46   719.6 2669.28   749.6 2682.75
   769.5 2690.25   789.5 2696.36   799.5 2698.68   809.5 2700.16   819.5 2700.71
#Mann= 3 , 0 , 0
       0      .1       0   402.1    .045       0   417.1      .1       0
Bank Sta=402.1,417.1
XS Rating Curve= 0 ,0
Exp/Cntr=0.3,0.1

Type RM Length L Ch R = 1 ,19897.6 ,435.2,448.9,462.7
XS GIS Cut Line= 3
     2020204.059       329872.25     2020613.464      329863.446
     2021022.869      329854.642
#Sta/Elev= 30
       0 2706.94      10 2700.98      30    2687      40 2679.18    89.9 2637.33
   109.9 2622.11   119.8 2615.27   129.8 2609.06   149.8 2598.03   179.8 2583.48
   199.8 2575.47   219.7 2568.48   299.6 2545.78   319.6 2542.76     402 2533.06
   409.5 2532.66     417 2533.68   419.5 2534.02   449.4 2545.63   479.4 2551.31
   489.4  2554.6   509.4 2562.85   519.4 2565.73   559.3  2569.3   649.2 2573.22
   689.2 2576.37   709.1 2579.15     789 2595.75     799 2597.03     819 2597.52
#Mann= 3 , 0 , 0
       0      .1       0     402    .045       0     417      .1       0
Bank Sta=402,417
XS Rating Curve= 0 ,0
Exp/Cntr=0.3,0.1

Type RM Length L Ch R = 1 ,19449.1 ,324.9,316.1,307.2
XS GIS Cut Line= 2
     2020183.524      330035.759     2020883.361      330499.475
#Sta/Elev= 30
       0 2718.68      10 2714.73      30 2704.24      90 2668.23   109.9 2654.28
   149.9 2623.13   179.9 2601.87   189.9  2595.3   209.9 2583.48   229.9 2573.32
   239.9  2569.1   259.8 2561.83   289.8 2552.82   309.8 2547.88   379.8 2532.27
   409.8 2523.92   417.9 2522.83   419.8 2522.58   432.9 2523.14   469.7 2527.54
   539.7  2534.8   549.7 2535.34   559.7  2535.2   609.7 2532.73   619.6 2533.23
   729.6  2549.2   739.6  2551.1   759.6 2556.72   789.6 2566.69   839.5 2584.11
#Mann= 3 , 0 , 0
       0      .1       0   417.9    .045       0   432.9      .1       0
Bank Sta=417.9,432.9
XS Rating Curve= 0 ,0
Exp/Cntr=0.3,0.1

Type RM Length L Ch R = 1 ,19132.6 ,422.7,435,445.8
XS GIS Cut Line= 2
     2020048.036       330476.29     2020831.166      330626.077
#Sta/Elev= 30
       0 2584.77    29.9 2570.54    39.9 2566.75    49.8  2563.9    89.7 2553.41
   139.5 2541.17   149.5  2538.9   159.5 2536.96   179.4 2533.51   199.3 2530.62
   259.1 2522.92   269.1 2521.94   348.8    2518   368.8 2516.57   378.6 2515.53
   388.7 2514.76   393.6  2514.9   398.7 2515.04   408.6 2516.24   428.6 2518.99
   508.3 2528.71   558.1 2535.12   578.1 2538.01     598 2541.57   617.9 2545.56
   647.8 2552.21   747.5 2576.62   757.5 2579.25   767.4 2582.16   797.3 2592.49
#Mann= 3 , 0 , 0
       0      .1       0   378.6    .045       0   393.6      .1       0
Bank Sta=378.6,393.6
XS Rating Curve= 0 ,0
Exp/Cntr=0.3,0.1

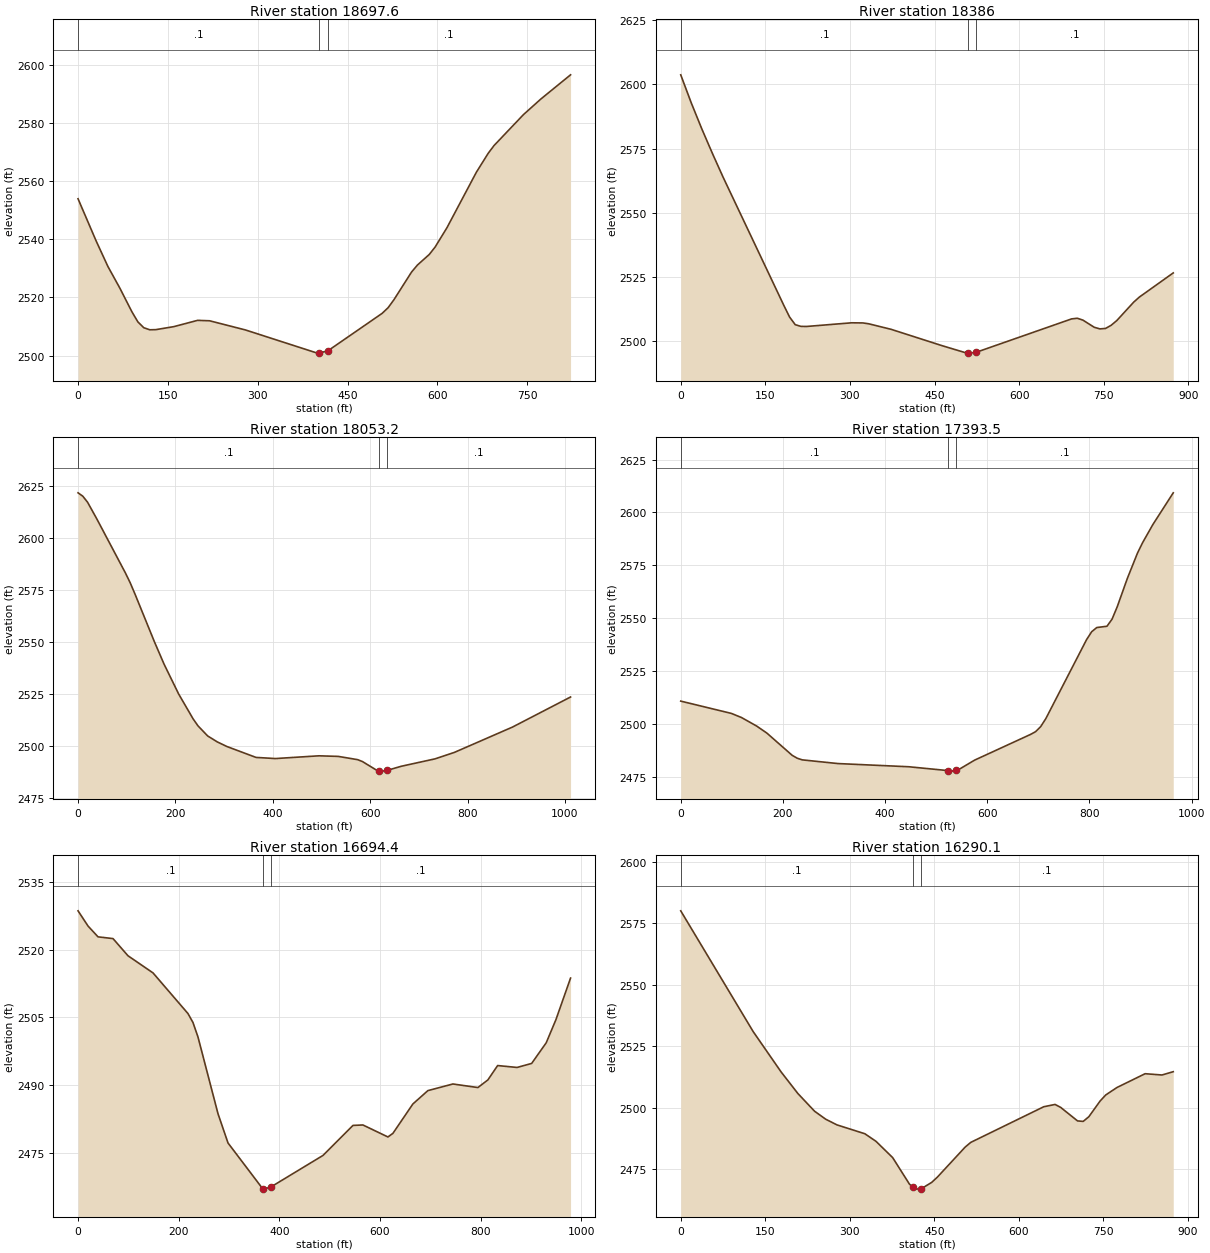
Type RM Length L Ch R = 1 ,18697.6 ,307.5,311.6,317
XS GIS Cut Line= 3
       2019938.7      330661.923     2020243.158        330935.7
     2020566.623      331192.222
#Sta/Elev= 30
       0 2553.96      30 2539.55    49.9 2530.65    69.9 2523.17    89.9 2515.08
    99.9 2511.59   109.8 2509.58   119.8 2508.87   129.8 2508.92   159.8 2509.95
   199.7 2512.12   219.7 2511.97   279.6 2508.81   399.5 2500.84   401.9 2500.86
   416.9  2501.6   507.7 2514.52   517.6 2516.45   527.4 2519.21   556.9 2528.76
   566.7 2531.16   586.4 2534.79   596.2 2537.35   615.9 2543.98     665 2563.07
   684.7 2569.57   694.5 2572.26   743.6  2582.9   773.1 2588.35   822.3 2596.61
#Mann= 3 , 0 , 0
       0      .1       0   401.9    .045       0   416.9      .1       0
Bank Sta=401.9,416.9
XS Rating Curve= 0 ,0
Exp/Cntr=0.3,0.1

Type RM Length L Ch R = 1 ,18386   ,344.8,332.6,320.3
XS GIS Cut Line= 3
     2019714.298      330738.771     2019777.888      330832.127
     2020244.649      331432.161
#Sta/Elev= 30
       0 2603.74    18.8 2592.72    37.6 2582.55    56.5 2572.93    75.3 2563.75
     183 2513.76     193 2509.31     203 2506.34     213 2505.68     223 2505.64
     303 2507.07     323 2507.02     333  2506.7     373 2504.53     463 2498.18
   503.1 2495.53   509.1 2495.36   513.1 2495.25   524.1  2495.6   693.1  2508.6
   703.1 2508.84   713.1 2508.11   733.1 2505.33   743.1  2504.7   753.1 2504.87
   763.1  2506.1   773.1 2507.94   803.1 2515.13   813.1  2517.1   873.2 2526.52
#Mann= 3 , 0 , 0
       0      .1       0   509.1    .045       0   524.1      .1       0
Bank Sta=509.1,524.1
XS Rating Curve= 0 ,0
Exp/Cntr=0.3,0.1

Type RM Length L Ch R = 1 ,18053.2 ,648,659.4,670.9
XS GIS Cut Line= 3
     2019241.201      331137.903     2019338.617      331182.552
     2020177.542       331519.93
#Sta/Elev= 30
       0 2621.77     9.7 2620.17    19.5 2617.27      39 2609.03    97.4 2583.15
   107.2 2578.42   117.1 2572.96   156.8  2550.1   176.7 2539.29   206.5 2524.99
   236.3 2512.97   246.3 2509.62   266.1 2504.76     286 2501.87   305.9 2499.64
   365.5 2494.41   405.3 2493.86   494.7 2495.18   534.4  2494.9   574.2 2493.33
   584.1 2492.41   613.9 2488.15     619 2487.98   623.9 2487.81     634 2488.12
   663.6 2490.14   733.2 2493.72   772.9 2496.83   892.2 2509.02  1011.4 2523.49
#Mann= 3 , 0 , 0
       0      .1       0     619    .045       0     634      .1       0
Bank Sta=619,634
XS Rating Curve= 0 ,0
Exp/Cntr=0.3,0.1

Type RM Length L Ch R = 1 ,17393.5 ,707.1,698.4,689.7
XS GIS Cut Line= 3
     2019203.317      331518.997      2019633.87      332012.087
      2019900.86      332168.433
#Sta/Elev= 30
       0 2510.78    99.2 2504.96     119 2503.01   148.8 2498.95   168.6 2495.66
   218.2 2485.13   228.1 2483.76     238 2482.99   307.5 2481.25   446.3 2479.74
   523.9  2477.9   535.6 2477.67   538.9 2477.98   545.5 2478.61   575.3 2482.88
   684.6 2495.02   694.5 2496.32   704.5 2498.71   714.5 2502.46   794.3 2539.83
   804.3 2543.58   814.3 2545.57   834.3 2546.19   844.2 2549.52   854.2  2555.3
   874.2 2568.83   894.1 2580.84   904.1 2585.75   924.1 2594.28     964 2609.28
#Mann= 3 , 0 , 0
       0      .1       0   523.9    .045       0   538.9      .1       0
Bank Sta=523.9,538.9
XS Rating Curve= 0 ,0
Exp/Cntr=0.3,0.1

Type RM Length L Ch R = 1 ,16694.4 ,420,404.2,388.5
XS GIS Cut Line= 3
     2018740.706      332029.962     2019453.471      332423.998
     2019595.453      332506.632
#Sta/Elev= 30
       0 2528.66    19.9 2525.28    39.7 2522.89    69.5  2522.5    99.3 2518.69
     149 2514.89   218.5 2505.87   228.4 2503.89   238.4 2500.66   278.1 2483.67
     298 2477.17   367.5 2466.93   367.8 2466.93   382.8 2467.38   486.7  2474.4
   546.3 2481.06   566.1 2481.16   615.8  2478.5   625.7  2479.3   665.4 2485.82
   695.2 2488.78   744.9 2490.25   794.6 2489.46   814.4 2491.15   833.8 2494.34
   872.4 2493.92   901.4 2494.81   930.4  2499.4   949.7 2504.54   978.7 2513.74
#Mann= 3 , 0 , 0
       0      .1       0   367.8    .045       0   382.8      .1       0
Bank Sta=367.8,382.8
XS Rating Curve= 0 ,0
Exp/Cntr=0.3,0.1

Type RM Length L Ch R = 1 ,16290.1 ,311.9,326.4,342.4
XS GIS Cut Line= 3
     2018743.095      332672.123      2019276.68       332564.71
     2019604.049      332602.056
#Sta/Elev= 30
       0 2580.06   128.6 2530.96   178.1 2514.59   207.8 2505.83   237.5 2498.62
   257.3 2495.37   277.1 2493.08   326.6 2489.48   346.4  2486.4     376 2479.78
   405.7 2469.03   411.6  2467.8   415.6 2466.97   426.6  2467.1   445.3 2469.72
   455.2 2471.82   504.7 2484.07   514.6 2485.97   644.1 2500.45   664.1 2501.38
   674.1 2500.18     704 2494.69     714 2494.49     724 2496.38     744 2502.76
     754 2505.23   773.9 2508.26   823.9 2513.87   853.8 2513.35   873.8 2514.69
#Mann= 3 , 0 , 0
       0      .1       0   411.6    .045       0   426.6      .1       0
Bank Sta=411.6,426.6
XS Rating Curve= 0 ,0
Exp/Cntr=0.3,0.1

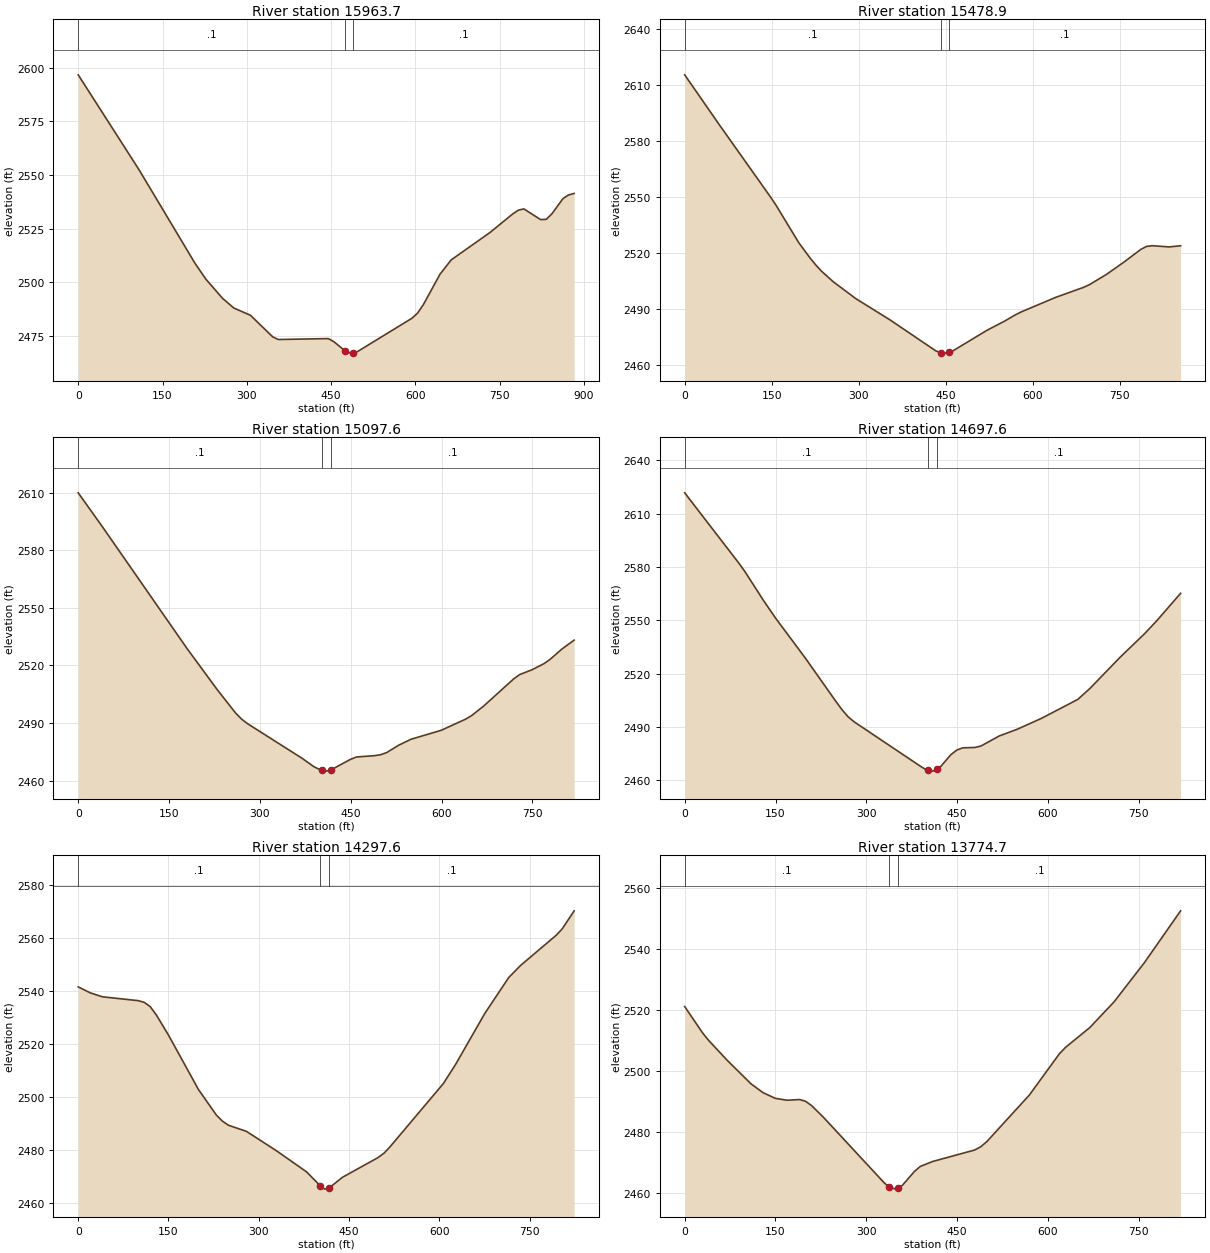
Type RM Length L Ch R = 1 ,15963.7 ,486.6,484.7,481.1
XS GIS Cut Line= 3
     2018721.762      332780.547      2019173.57      332889.423
      2019536.35      333096.393
#Sta/Elev= 30
       0 2596.74   108.8 2552.19   207.6 2508.86   227.4 2501.28   257.1 2492.35
   276.9 2487.91   306.5  2484.5   346.1 2474.43     356 2473.21     445 2473.63
   454.8 2472.21     474 2468.07   484.6 2466.85     489    2467   494.6  2467.2
     594 2483.16     604 2485.58   613.9 2489.38   643.7 2503.66   663.6 2510.36
   733.2 2523.25     773  2531.8     783 2533.55   792.9 2534.17   822.7 2529.18
   832.7 2529.29   842.6  2531.8   862.5 2538.97   872.5 2540.68   882.4 2541.37
#Mann= 3 , 0 , 0
       0      .1       0     474    .045       0     489      .1       0
Bank Sta=474,489
XS Rating Curve= 0 ,0
Exp/Cntr=0.3,0.1

Type RM Length L Ch R = 1 ,15478.9 ,379.6,381.4,383.1
XS GIS Cut Line= 3
     2018687.538      333127.701     2019038.185      333257.671
     2019485.034      333436.305
#Sta/Elev= 30
       0 2615.48      59 2589.04   147.6 2550.16   157.5 2545.58   196.8 2525.46
   216.5 2517.16   226.3 2513.47   236.2 2510.14   255.9 2504.61   295.2 2495.48
   354.3 2484.06   432.9 2467.52   441.4 2466.45   452.5 2466.28   456.4 2466.74
   462.4 2467.46   521.3 2478.53   550.7 2483.26   570.4 2486.84   580.2 2488.36
   639.1 2496.09   688.2 2501.58     698 2502.98   727.5 2508.52     757 2514.97
   786.4 2521.86   796.3 2523.46   806.1 2523.87   835.6 2523.22   855.2 2523.84
#Mann= 3 , 0 , 0
       0      .1       0   441.4    .045       0   456.4      .1       0
Bank Sta=441.4,456.4
XS Rating Curve= 0 ,0
Exp/Cntr=0.3,0.1

Type RM Length L Ch R = 1 ,15097.6 ,390,400,409.8
XS GIS Cut Line= 3
     2018584.694      333452.067     2018952.582      333631.923
     2019320.471      333811.779
#Sta/Elev= 30
       0 2609.92      40 2592.22   179.8 2528.76   229.7 2507.33   259.7 2495.29
   269.7 2492.06   279.7 2489.64   369.6 2471.64   389.5 2467.17     402  2465.3
   409.5 2464.93     417 2465.49   449.4 2471.02   459.4 2472.29   489.4 2472.99
   499.4 2473.46   509.4  2474.6   529.4 2478.45   549.3 2481.51   599.3 2486.18
   639.2 2491.92   649.2 2493.75   669.2 2498.73   719.1 2512.96   729.1 2515.25
   749.1 2517.69   769.1 2520.91     779 2523.09     799  2528.6     819 2533.19
#Mann= 3 , 0 , 0
       0      .1       0     402    .045       0     417      .1       0
Bank Sta=402,417
XS Rating Curve= 0 ,0
Exp/Cntr=0.3,0.1

Type RM Length L Ch R = 1 ,14697.6 ,413.3,400,389.9
XS GIS Cut Line= 3
     2018450.102      333619.094     2018704.733      333939.822
     2018961.905      334258.492
#Sta/Elev= 30
       0 2621.76    89.9 2581.99    99.9 2577.22   129.8 2561.36   149.8 2551.38
   199.8 2528.49   249.7 2504.35   259.7 2499.74   269.7 2495.77   279.7 2492.89
   389.5  2467.8   399.5 2465.74     402 2465.58   409.5  2465.1     417 2466.06
   419.5 2466.38   439.5 2474.32   449.5 2476.99   459.4 2478.21   479.4 2478.42
   489.4 2479.25   519.4 2484.88   549.3 2488.69   589.3 2494.82   649.2 2505.47
   669.2 2511.62   719.1 2529.21   759.1 2542.33   779.1 2549.55     819  2565.2
#Mann= 3 , 0 , 0
       0      .1       0     402    .045       0     417      .1       0
Bank Sta=402,417
XS Rating Curve= 0 ,0
Exp/Cntr=0.3,0.1

Type RM Length L Ch R = 1 ,14297.6 ,514.4,522.9,528.4
XS GIS Cut Line= 3
     2018045.993      334089.056      2018435.62      334214.643
     2018810.124      334392.626
#Sta/Elev= 30
       0 2541.47      20 2539.21    39.9 2537.73    99.8 2536.26   109.8 2535.63
   119.8 2533.97   129.8 2530.89   149.8 2523.38   199.7 2502.85   229.6 2493.16
   239.6 2490.91   249.6 2489.36   279.6 2487.04   329.5 2479.73   379.4  2471.8
   401.9 2466.62   409.4  2465.3   416.9 2465.74     439 2469.75   498.2 2477.18
   508.1 2478.84     518 2481.21   606.8 2505.08   626.6  2512.1   675.9 2531.58
   715.4 2544.99   735.2 2549.57   794.4 2560.93   804.3 2563.34     824 2570.09
#Mann= 3 , 0 , 0
       0      .1       0   401.9    .045       0   416.9      .1       0
Bank Sta=401.9,416.9
XS Rating Curve= 0 ,0
Exp/Cntr=0.3,0.1

Type RM Length L Ch R = 1 ,13774.7 ,655.1,650.5,646.5
XS GIS Cut Line= 3
     2017867.752      334413.253     2018184.894      334672.145
     2018489.499      334946.728
#Sta/Elev= 30
       0 2521.12      30 2512.37    39.9 2509.97    69.9 2503.57   109.8 2495.76
   129.8 2492.86   149.8 2491.03   169.8  2490.4   189.7 2490.64   199.7 2490.08
   209.7 2488.66   229.7 2484.74   329.5 2463.39   338.3 2461.85   349.5 2461.28
   353.3 2461.73   359.5 2462.47   379.4 2467.02   389.4 2468.72   409.4 2470.32
   479.4 2474.11   489.4 2475.18   499.4 2476.88   569.4 2492.08   619.4 2505.69
   629.4 2507.75   669.5 2514.24   709.5 2522.65   759.5 2535.46   819.5 2552.49
#Mann= 3 , 0 , 0
       0      .1       0   338.3    .045       0   353.3      .1       0
Bank Sta=338.3,353.3
XS Rating Curve= 0 ,0
Exp/Cntr=0.3,0.1

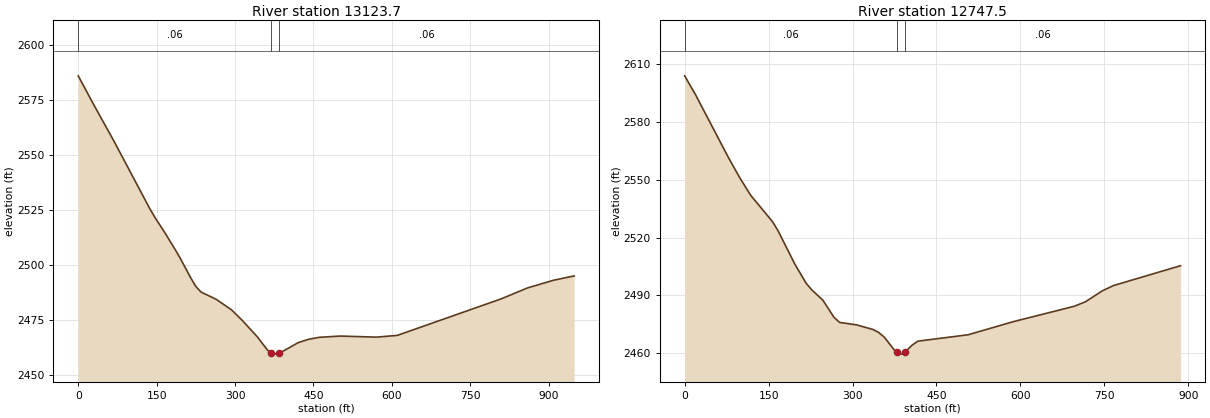
Type RM Length L Ch R = 1 ,13123.7 ,386.8,376.1,364.7
XS GIS Cut Line= 3
     2017299.589      334749.501     2017636.017      334929.325
     2018125.008      335216.809
#Sta/Elev= 30
       0 2586.07    29.3 2573.12    68.5 2556.34   136.9 2525.72   146.7 2521.75
   166.3 2514.57   185.8    2507   195.6 2502.99   215.2  2494.3     225 2490.36
   234.8 2487.84   264.1  2484.5   293.4  2479.7     313 2475.13   342.4 2467.53
   361.9 2461.51   369.5 2460.08   371.7 2459.67   381.5 2459.61   384.5 2459.97
   421.3 2464.89   441.2 2466.37   461.1 2467.24   500.9 2467.82   570.6 2467.33
   610.4 2468.12   809.4 2484.74   859.2 2489.66   908.9 2493.16   948.7 2495.15
#Mann= 3 , 0 , 0
       0     .06       0   369.5    .045       0   384.5     .06       0
Bank Sta=369.5,384.5
XS Rating Curve= 0 ,0
Exp/Cntr=0.3,0.1

Type RM Length L Ch R = 1 ,12747.5 ,449.9,449.8,450.3
XS GIS Cut Line= 3
      2017202.09      335295.952     2017359.038       335290.54
     2018088.119      335305.503
#Sta/Elev= 30
       0 2603.89    19.6 2593.98    78.5 2561.33    98.2 2551.14   117.8 2541.98
     157 2528.22     167 2523.46     197 2506.13     217 2496.32     227 2492.87
     247 2487.48   266.9 2478.59   276.9 2475.95   306.9  2474.7   336.8 2472.26
   346.8 2470.72   356.8 2468.28   376.8 2460.85   379.5 2460.49   386.8  2459.5
   394.5 2460.79   406.8 2464.24   416.8 2466.23   506.7 2469.55   586.6 2476.29
   696.5 2484.35   716.4  2486.7   746.4 2492.34   766.4 2495.09   886.3 2505.38
#Mann= 3 , 0 , 0
       0     .06       0   379.5    .045       0   394.5     .06       0
Bank Sta=379.5,394.5
XS Rating Curve= 0 ,0
Exp/Cntr=0.3,0.1