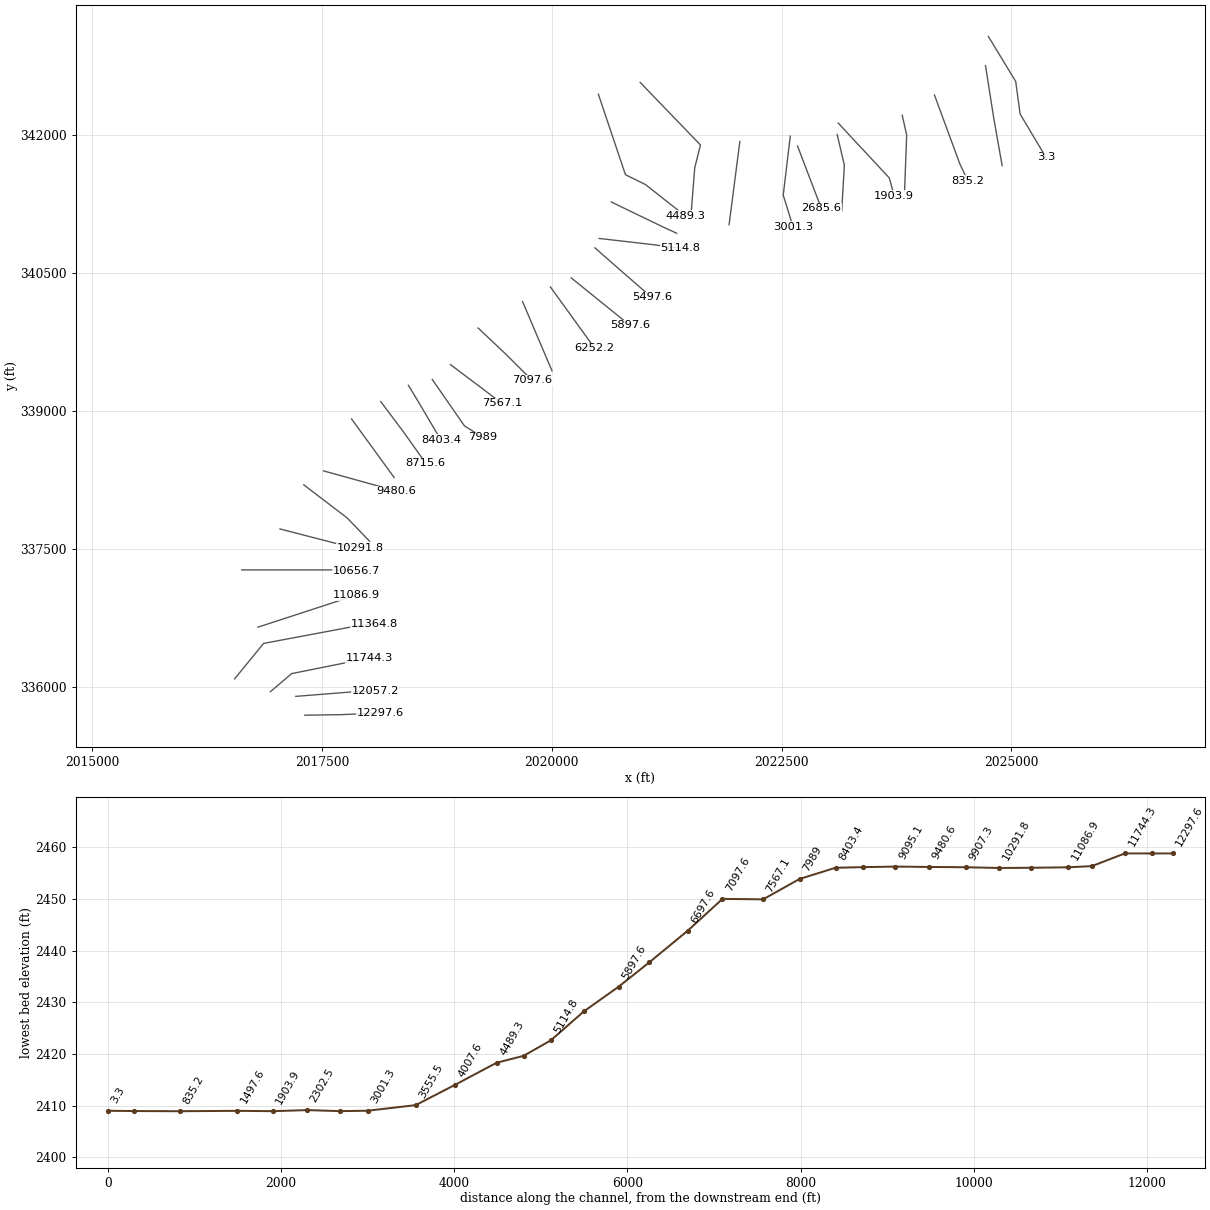
HEC-RAS study SewellCrk.prj: SewellCrk

--- SewellCrk.g01 (geometry) --- (continued)

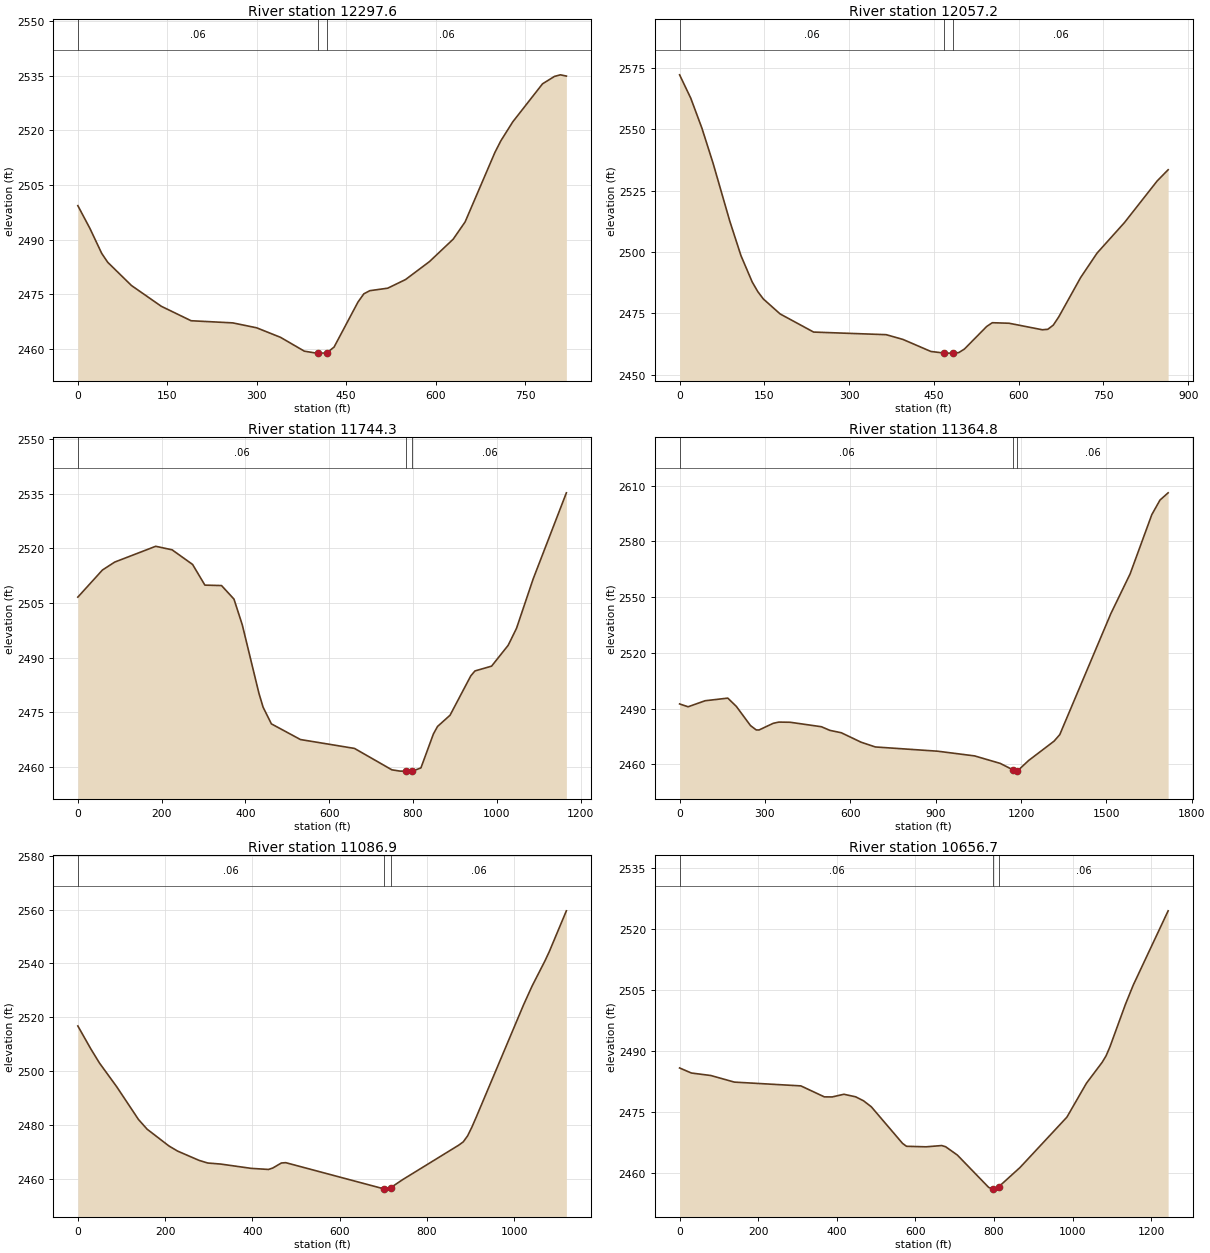
Type RM Length L Ch R = 1 ,12297.6 ,239,240.5,241.2
XS GIS Cut Line= 3
     2017314.781      335691.235     2017724.468      335697.634
     2018133.484      335716.657
#Sta/Elev= 30
       0 2499.29      20 2493.13      40 2486.21      50 2483.77    89.9 2477.38
   139.9 2471.68   189.9 2467.71   259.8 2467.12   299.8 2465.77   339.8 2463.16
   379.8 2459.36   399.7 2458.82   402.2 2458.82   417.2 2458.84   429.7 2460.49
   469.7 2472.82   479.6  2475.1   489.6 2475.96   519.6 2476.64   549.6 2479.02
   589.5 2483.92   629.4 2490.09   649.4 2494.83   699.4 2513.91   709.3 2517.09
   729.3 2522.29   779.2 2532.73   799.2 2534.76   809.2  2535.2   819.2 2534.86
#Mann= 3 , 0 , 0
       0     .06       0   402.2    .045       0   417.2     .06       0
Bank Sta=402.2,417.2
XS Rating Curve= 0 ,0
Exp/Cntr=0.3,0.1

Type RM Length L Ch R = 1 ,12057.2 ,310.4,312.9,315.3
XS GIS Cut Line= 3
     2017216.462      335896.199     2017837.095      335945.388
      2018078.83      335958.016
#Sta/Elev= 30
       0 2572.22    19.8 2562.68    39.5 2550.48    59.3 2536.14    88.9 2512.53
   108.7 2498.47   128.5  2487.8   138.4 2483.87   148.2 2480.88   177.9 2474.78
   237.2 2467.39   365.6 2466.33   395.3 2464.39   444.7 2459.49   468.6 2458.82
   483.6 2458.81   494.1 2459.03     504 2460.46   543.5 2469.68   553.4  2471.2
     583 2470.99     642 2468.33   651.6 2468.52   661.3 2470.21     671 2473.57
   709.7  2489.6   738.8 2499.57   787.2 2511.98   845.3    2529   864.6 2533.53
#Mann= 3 , 0 , 0
       0     .06       0   468.6    .045       0   483.6     .06       0
Bank Sta=468.6,483.6
XS Rating Curve= 0 ,0
Exp/Cntr=0.3,0.1

Type RM Length L Ch R = 1 ,11744.3 ,379.5,379.4,379.3
XS GIS Cut Line= 3
     2016940.512      335947.192     2017171.423      336143.827
     2018017.494      336313.402
#Sta/Elev= 30
       0 2506.63    58.7 2514.08      88 2516.26   185.9  2520.6     225 2519.63
   273.9 2515.61   303.3 2509.93     343 2509.81   372.7 2506.09   392.6    2499
   432.2 2480.25   442.2  2476.4     462 2471.81   531.4  2467.5   660.4 2465.06
   749.6 2459.18   769.4 2458.82   783.8 2458.82   798.8 2458.82     819 2459.71
   848.8 2469.04   858.7  2471.1   888.5 2474.18   938.1 2485.01     948 2486.35
   987.7 2487.67  1027.3  2493.4  1047.2 2498.07  1086.8 2511.59  1166.2 2535.29
#Mann= 3 , 0 , 0
       0     .06       0   783.8    .045       0   798.8     .06       0
Bank Sta=783.8,798.8
XS Rating Curve= 0 ,0
Exp/Cntr=0.3,0.1

Type RM Length L Ch R = 1 ,11364.8 ,274.9,277.8,280.8
XS GIS Cut Line= 4
      2016550.85      336086.099     2016866.217      336472.116
     2017885.803      336663.376     2018066.202       336683.22
#Sta/Elev= 30
       0 2492.52    29.9    2491    89.7 2494.24   169.5 2495.65   199.4  2491.2
   249.2 2480.87   269.2 2478.55   279.1 2478.49     329 2482.09   348.9 2482.75
   388.8 2482.66   498.5 2480.25   528.4 2478.29   568.3 2477.02   638.1 2471.92
     688 2469.37   907.4 2467.08  1037.1 2464.55  1126.9 2460.53  1172.6 2456.99
  1186.7 2456.36  1187.6 2456.44  1226.6 2462.04  1316.4  2472.5  1336.3 2475.99
  1515.9 2541.12  1583.6 2562.49    1660 2594.43  1688.7 2602.25  1717.3 2606.14
#Mann= 3 , 0 , 0
       0     .06       0  1172.6    .045       0  1187.6     .06       0
Bank Sta=1172.6,1187.6
XS Rating Curve= 0 ,0
Exp/Cntr=0.3,0.1

Type RM Length L Ch R = 1 ,11086.9 ,437.8,430.2,422.7
XS GIS Cut Line= 3
     2016805.212      336648.945     2017701.796      336941.191
     2017869.771      336996.111
#Sta/Elev= 30
       0 2516.75    29.8 2508.22    49.6 2502.98    89.3 2494.12     139    2482
   158.8  2478.4   208.5  2472.2   228.3 2470.29   277.9 2466.81   297.8 2465.83
   327.6 2465.44   397.1 2463.85   436.8 2463.44   446.7 2463.96   466.5 2465.84
   476.5 2465.96   702.6 2456.18   704.8 2456.13   717.6 2456.73   744.5 2459.66
   873.5 2472.52   883.4  2473.7   893.4 2475.94   903.3 2479.22   913.2 2482.91
  1021.6 2524.61  1041.2 2531.61  1070.6 2540.93  1080.5 2544.36  1119.7 2559.53
#Mann= 3 , 0 , 0
       0     .06       0   702.6    .045       0   717.6     .06       0
Bank Sta=702.6,717.6
XS Rating Curve= 0 ,0
Exp/Cntr=0.3,0.1

Type RM Length L Ch R = 1 ,10656.7 ,369.7,364.3,359
XS GIS Cut Line= 3
     2016628.421      337271.321     2017723.444      337271.321
     2017871.371      337264.105
#Sta/Elev= 30
       0 2485.85    29.9 2484.61    79.6 2483.99   139.4 2482.37   308.6 2481.44
   368.3 2478.74   388.2 2478.72   418.1 2479.38     448 2478.75   467.9 2477.78
   487.8  2476.3   567.4 2467.28   577.4 2466.58   627.2 2466.45     667 2466.76
   676.9 2466.47   706.8 2464.42   786.4 2456.47   796.4 2456.04   797.6 2456.07
   812.6 2456.67   866.1 2461.35   985.5 2473.75  1035.3 2482.11  1075.1 2487.22
  1085.1 2488.82    1095 2491.05  1134.5 2501.52  1154.3 2506.23  1243.1 2524.51
#Mann= 3 , 0 , 0
       0     .06       0   797.6    .045       0   812.6     .06       0
Bank Sta=797.6,812.6
XS Rating Curve= 0 ,0
Exp/Cntr=0.3,0.1

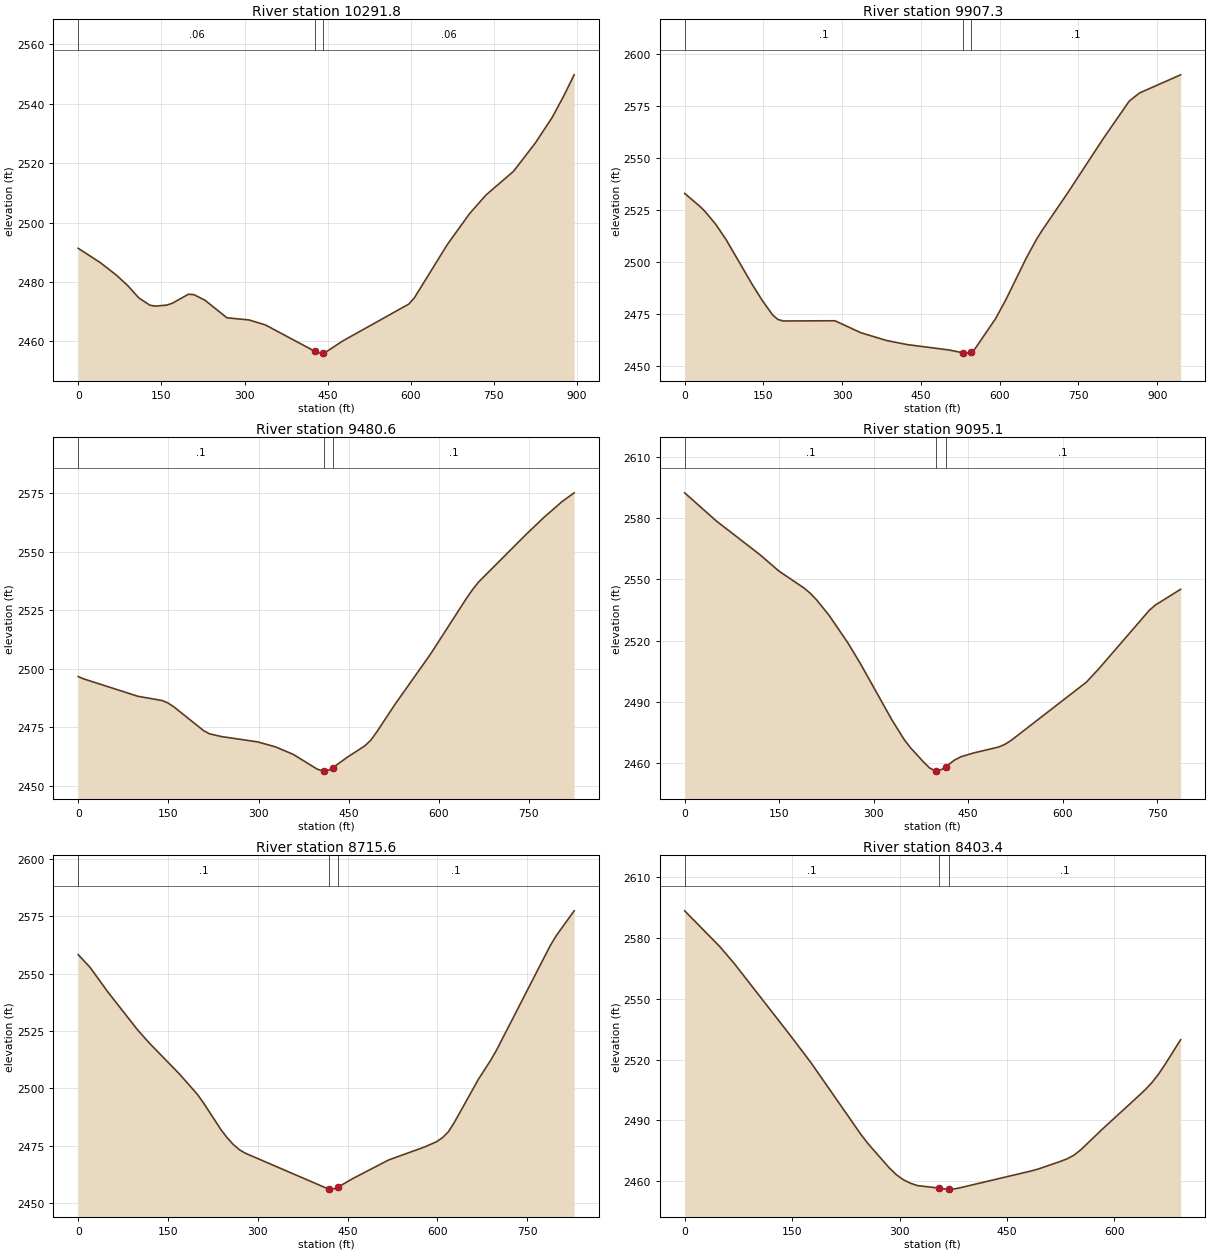
Type RM Length L Ch R = 1 ,10291.8 ,393.5,384.5,375.4
XS GIS Cut Line= 3
     2017045.143      337716.907     2017651.284       337559.96
     2017914.667      337507.644
#Sta/Elev= 30
       0 2491.32    39.8  2486.5    69.6 2482.16    89.4 2478.74   109.3 2474.61
   129.2 2472.16   139.1 2471.83     159 2472.16     169 2472.73   198.8 2475.84
   208.7 2475.71   228.6 2473.83   268.3  2467.9   308.1 2467.18   337.9 2465.49
   427.1 2456.58   437.3    2456   442.1  2456.2   447.2 2456.41     477 2460.08
   596.3 2472.51   606.2 2474.56   665.9 2492.58   705.7 2502.92   735.5 2509.25
   785.3 2517.25     825 2526.88   854.9 2535.36   874.8 2542.23   894.7 2549.76
#Mann= 3 , 0 , 0
       0     .06       0   427.1    .045       0   442.1     .06       0
Bank Sta=427.1,442.1
XS Rating Curve= 0 ,0
Exp/Cntr=0.3,0.1

Type RM Length L Ch R = 1 ,9907.3  ,418.2,426.6,435.1
XS GIS Cut Line= 3
     2017303.114      338196.768     2017773.955      337837.774
     2018018.396      337583.875
#Sta/Elev= 30
       0 2533.01    29.6 2526.66    39.5 2524.13    59.2 2518.13      79 2510.74
   128.3 2489.34     148 2481.41   167.8 2474.44   177.6 2472.34   187.5 2471.62
   286.2 2471.72   335.5 2465.96   384.9 2462.19   424.3 2460.23   503.3 2457.66
     530  2456.3   532.9 2456.14   542.8  2456.2     545 2456.63   552.6 2458.12
   592.1 2472.74   611.7 2481.86   650.8 2502.02   670.4 2511.07   680.2    2515
   729.2 2533.18   797.7  2559.6   846.6 2577.44   866.2 2581.36   944.5  2590.1
#Mann= 3 , 0 , 0
       0      .1       0     530    .045       0     545      .1       0
Bank Sta=530,545
XS Rating Curve= 0 ,0
Exp/Cntr=0.3,0.1

Type RM Length L Ch R = 1 ,9480.6  ,400.7,385.5,370.3
XS GIS Cut Line= 2
     2017518.335      338348.197     2018313.673      338128.184
#Sta/Elev= 30
       0 2496.61     9.9 2495.56    99.4 2488.18   139.2  2486.4   149.1 2485.37
   159.1 2483.69   208.8 2473.48   218.7 2472.13   238.6 2470.96   298.3 2468.71
   328.1 2466.59   357.9 2463.34   397.7 2457.04   407.6  2456.2   408.2 2456.23
   417.6 2456.69   423.2  2457.6   447.4 2462.08   477.2 2467.06   487.2 2469.52
   497.1 2473.09   526.9 2484.66   586.6 2506.37   646.2 2530.12   656.2 2533.79
   666.1    2537   745.7 2557.49   775.5 2564.78   805.3 2571.45   825.2 2575.15
#Mann= 3 , 0 , 0
       0      .1       0   408.2    .045       0   423.2      .1       0
Bank Sta=408.2,423.2
XS Rating Curve= 0 ,0
Exp/Cntr=0.3,0.1

Type RM Length L Ch R = 1 ,9095.1  ,379.3,379.4,379.2
XS GIS Cut Line= 2
     2017823.224      338912.578     2018286.289      338276.144
#Sta/Elev= 30
       0 2592.33    49.8 2578.68   119.6 2562.05   149.4 2554.11   189.3 2545.81
   199.3 2543.23   209.2 2540.06   229.2 2532.44     259 2518.99     279 2508.78
   328.8 2481.38   348.7 2471.54   358.7 2467.59   378.6  2460.9   388.6 2457.84
   398.5 2456.27   399.2 2456.33   408.5 2457.14   414.2  2458.4   428.4  2461.7
   438.4 2463.28   458.3 2465.13   498.1 2468.04   508.1 2469.35   518.1 2471.28
   637.6 2499.78   657.6 2506.42   737.2 2534.82   747.2  2537.5   787.1 2545.16
#Mann= 3 , 0 , 0
       0      .1       0   399.2    .045       0   414.2      .1       0
Bank Sta=399.2,414.2
XS Rating Curve= 0 ,0
Exp/Cntr=0.3,0.1

Type RM Length L Ch R = 1 ,8715.6  ,314.4,312.1,310.3
XS GIS Cut Line= 3
     2018140.208      339102.372     2018391.273      338767.367
     2018628.458      338432.843
#Sta/Elev= 30
       0 2558.28    19.9 2552.71    49.8 2541.94    99.7 2525.36   119.6 2519.58
   169.4 2506.23   199.4 2497.35   209.3 2493.74   239.2 2481.81   249.2 2478.46
   259.2 2475.59   269.1 2473.37   279.1 2471.82   418.6 2456.16   419.6 2456.18
   428.6 2456.36   434.6  2457.1   458.6 2460.73   518.7 2468.86   578.7 2474.51
   598.7  2476.8   608.7 2478.56   618.7 2481.18   628.7  2485.3   668.7    2504
   688.7 2512.07   698.7 2516.54   788.7 2562.18   798.7  2566.5   828.7 2577.36
#Mann= 3 , 0 , 0
       0      .1       0   419.6    .045       0   434.6      .1       0
Bank Sta=419.6,434.6
XS Rating Curve= 0 ,0
Exp/Cntr=0.3,0.1

Type RM Length L Ch R = 1 ,8403.4  ,412.7,414.3,415.8
XS GIS Cut Line= 3
     2018441.432      339279.163     2018547.867      339102.372
     2018795.014      338683.846
#Sta/Elev= 30
       0 2593.36    49.1 2575.69    68.8 2567.56   147.4 2531.92   176.9 2518.16
     246 2483.05     256 2478.47   285.7 2466.51   295.6 2463.15   305.6  2460.6
   315.5 2458.91   325.4 2457.76   354.4 2456.59   365.1 2456.04   369.4 2456.04
     375 2456.05   384.9 2456.74   484.1 2465.03     494    2466   523.8 2469.63
   533.7 2470.95   543.6 2472.81   553.5  2475.6   583.3 2485.69   632.9 2501.75
   642.8 2505.03   652.7 2508.76   662.6 2513.29   672.6 2518.64   692.4 2529.76
#Mann= 3 , 0 , 0
       0      .1       0   354.4    .045       0   369.4      .1       0
Bank Sta=354.4,369.4
XS Rating Curve= 0 ,0
Exp/Cntr=0.3,0.1

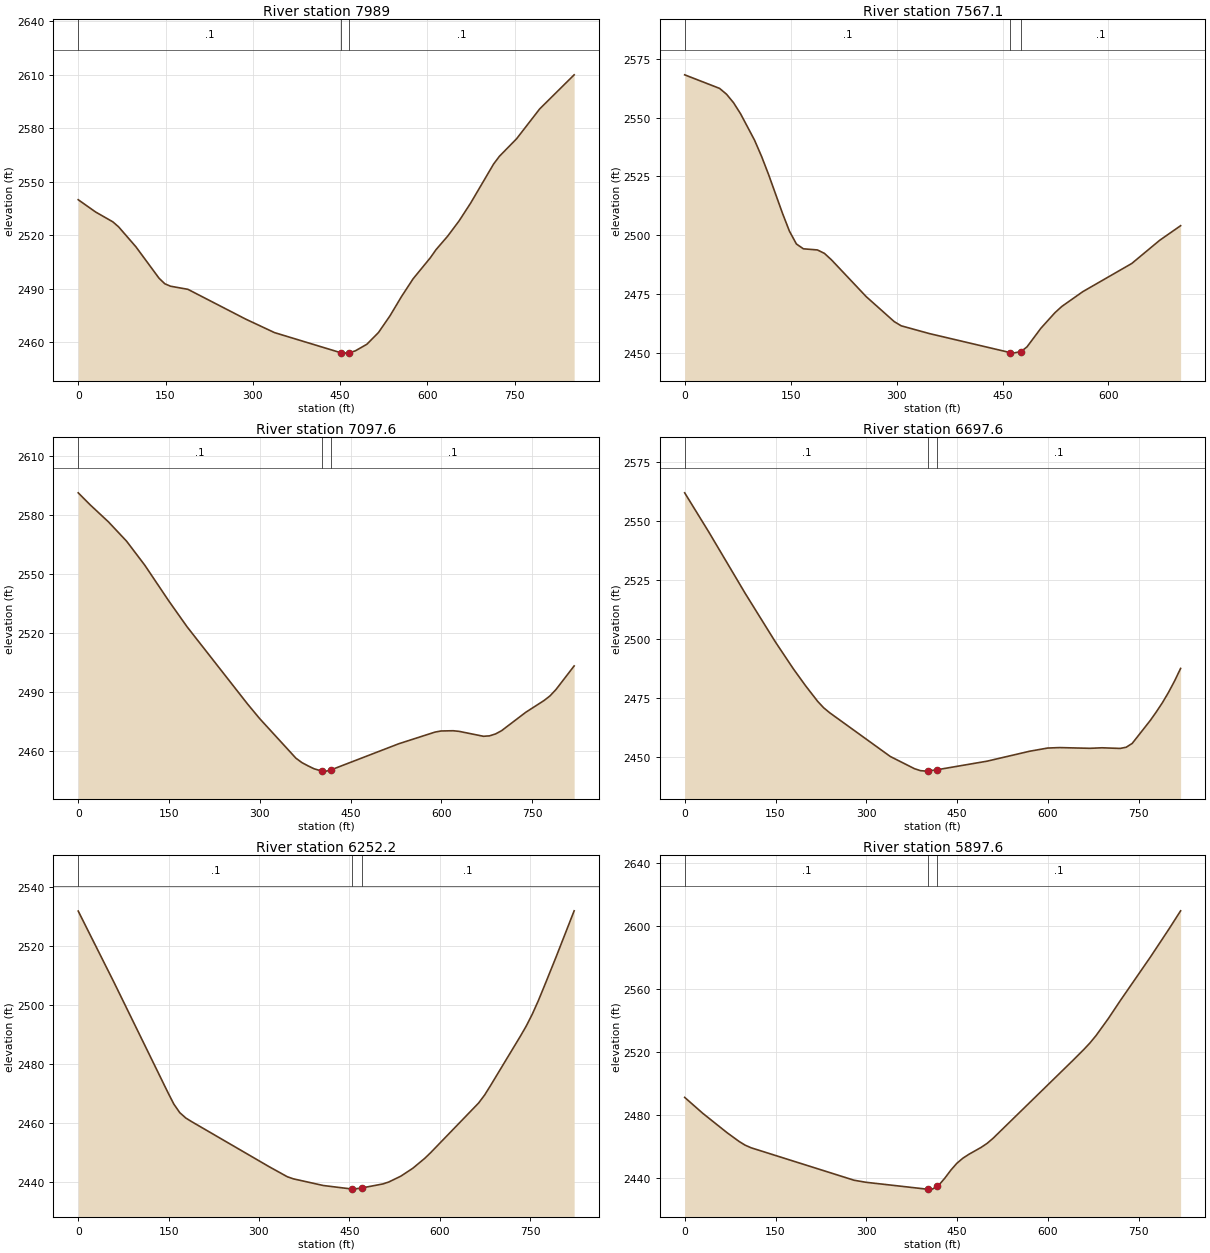
Type RM Length L Ch R = 1 ,7989    ,414.6,421.9,429.4
XS GIS Cut Line= 3
     2018700.731      339342.483     2019051.181      338837.185
     2019252.464      338711.878
#Sta/Elev= 30
       0 2539.84    29.8 2532.98    59.5 2527.44    69.4 2524.64    99.2 2513.43
   138.9 2495.84   148.8 2492.74   158.7 2491.36   188.4 2489.64   287.6 2472.96
   337.2 2465.38   450.9 2454.12   456.2 2453.88   465.9 2454.12   476.1 2455.16
   495.9 2458.85   515.8  2465.4   535.6 2474.78   555.4 2485.58   575.3 2495.51
     605 2507.34   614.9 2511.93   634.7 2519.42   654.4 2528.01   674.2 2537.96
   713.7 2559.88   723.6 2564.17   753.2 2574.03   792.8 2590.72     852 2609.82
#Mann= 3 , 0 , 0
       0      .1       0   450.9    .045       0   465.9      .1       0
Bank Sta=450.9,465.9
XS Rating Curve= 0 ,0
Exp/Cntr=0.3,0.1

Type RM Length L Ch R = 1 ,7567.1  ,471.9,469.4,466.3
XS GIS Cut Line= 2
     2018897.842      339504.662     2019458.883      339082.528
#Sta/Elev= 30
       0 2568.17    49.4 2562.41    59.3 2559.92    69.2 2556.31    79.1 2551.63
    98.9 2540.42   108.8 2533.56   118.7 2525.88   138.4  2509.4   148.3 2501.75
   158.2 2496.29   168.1 2494.25   187.9 2493.77   197.8 2492.32   207.7  2489.6
   257.1  2473.9   296.7 2463.31   306.6 2461.53   346.1 2458.26   461.2 2450.13
   464.8 2449.93   476.2  2450.6   484.6 2452.58   504.3  2460.5   524.1 2467.08
     534 2469.78   563.7 2476.06   632.9 2488.01   672.4 2497.85   702.1 2504.07
#Mann= 3 , 0 , 0
       0      .1       0   461.2    .045       0   476.2      .1       0
Bank Sta=461.2,476.2
XS Rating Curve= 0 ,0
Exp/Cntr=0.3,0.1

Type RM Length L Ch R = 1 ,7097.6  ,409.3,400,391.3
XS GIS Cut Line= 3
     2019200.031      339901.905      2019497.72      339620.754
     2019787.984       339331.65
#Sta/Elev= 30
       0 2591.09      20 2584.93    49.9 2576.38    79.9 2566.57   109.9 2554.43
   149.8  2536.2   179.8 2523.18   279.6 2484.07   299.6 2476.67   359.5 2456.59
   369.5 2454.32   379.5 2452.69   389.5 2451.21     402 2450.06   409.5 2450.01
     417 2450.58   529.4 2463.88   589.3  2469.8   599.3 2470.36   619.3 2470.48
   629.3 2470.16   669.3 2467.67   679.3 2467.89   689.2 2468.86   699.2  2470.5
   739.2 2479.84   769.2 2485.77   779.2 2488.14   789.2 2491.42   819.1 2503.34
#Mann= 3 , 0 , 0
       0      .1       0     402    .045       0     417      .1       0
Bank Sta=402,417
XS Rating Curve= 0 ,0
Exp/Cntr=0.3,0.1

Type RM Length L Ch R = 1 ,6697.6  ,440.3,445.4,450.5
XS GIS Cut Line= 3
     2019682.334      340190.529     2019842.507      339813.654
      2020002.68      339436.778
#Sta/Elev= 30
       0 2561.84      40 2545.17    99.9 2519.24   149.8 2498.63   179.8 2487.11
   199.8 2480.01   219.7 2473.42   229.7 2470.68   239.7 2468.57   339.6 2450.07
   379.5  2444.9   389.5 2444.06   399.5 2443.87     402 2443.93     417 2444.46
   499.4 2448.09   569.3 2452.28   599.3 2453.65   619.2 2453.85   669.2 2453.54
   689.2 2453.76   719.1 2453.49   729.1 2453.99   739.1 2455.63   769.1 2465.42
     779 2469.03     789 2472.91     799 2477.25     809 2482.07     819 2487.41
#Mann= 3 , 0 , 0
       0      .1       0     402    .045       0     417      .1       0
Bank Sta=402,417
XS Rating Curve= 0 ,0
Exp/Cntr=0.3,0.1

Type RM Length L Ch R = 1 ,6252.2  ,348.6,354.6,360.6
XS GIS Cut Line= 2
     2019985.648      340348.929     2020467.313      339681.453
#Sta/Elev= 30
       0 2531.93    59.5 2507.73   148.8 2470.49   158.7 2466.53   168.6 2463.62
   178.5 2461.82   188.4 2460.57   317.4 2445.26   347.1 2441.91     357 2441.21
   406.6 2438.95   455.2 2437.73   456.2 2437.72   470.2  2438.1   505.8 2439.48
   515.7 2440.16   535.5 2442.12   555.4  2444.8   575.2 2448.16   585.1 2450.11
   664.4 2466.86   674.4 2469.57   684.3  2472.8   733.9 2489.55   743.8 2493.05
   753.7 2497.03   763.6 2501.54   773.5 2506.45   793.4 2516.52   823.1 2532.01
#Mann= 3 , 0 , 0
       0      .1       0   455.2    .045       0   470.2      .1       0
Bank Sta=455.2,470.2
XS Rating Curve= 0 ,0
Exp/Cntr=0.3,0.1

Type RM Length L Ch R = 1 ,5897.6  ,400.9,400,399.2
XS GIS Cut Line= 3
     2020211.959      340446.912     2020530.631      340189.738
     2020849.303      339932.563
#Sta/Elev= 30
       0 2491.14      30 2481.01    69.9 2468.81    89.9 2463.21    99.9 2460.85
   109.9 2459.18   279.7 2438.64   299.6 2437.32   399.5    2433     402 2433.02
   409.5  2433.1     417 2434.86   419.5 2435.45   429.5  2439.9   439.5 2445.01
   449.4 2449.35   459.4  2452.6   469.4 2455.08   489.4 2459.42   499.4 2461.99
   509.4 2465.26   639.2 2513.87   659.2 2521.52   669.2 2525.61   679.2 2530.26
   699.2 2540.87   719.1 2552.31   769.1  2580.1     799 2597.41     819 2609.39
#Mann= 3 , 0 , 0
       0      .1       0     402    .045       0     417      .1       0
Bank Sta=402,417
XS Rating Curve= 0 ,0
Exp/Cntr=0.3,0.1

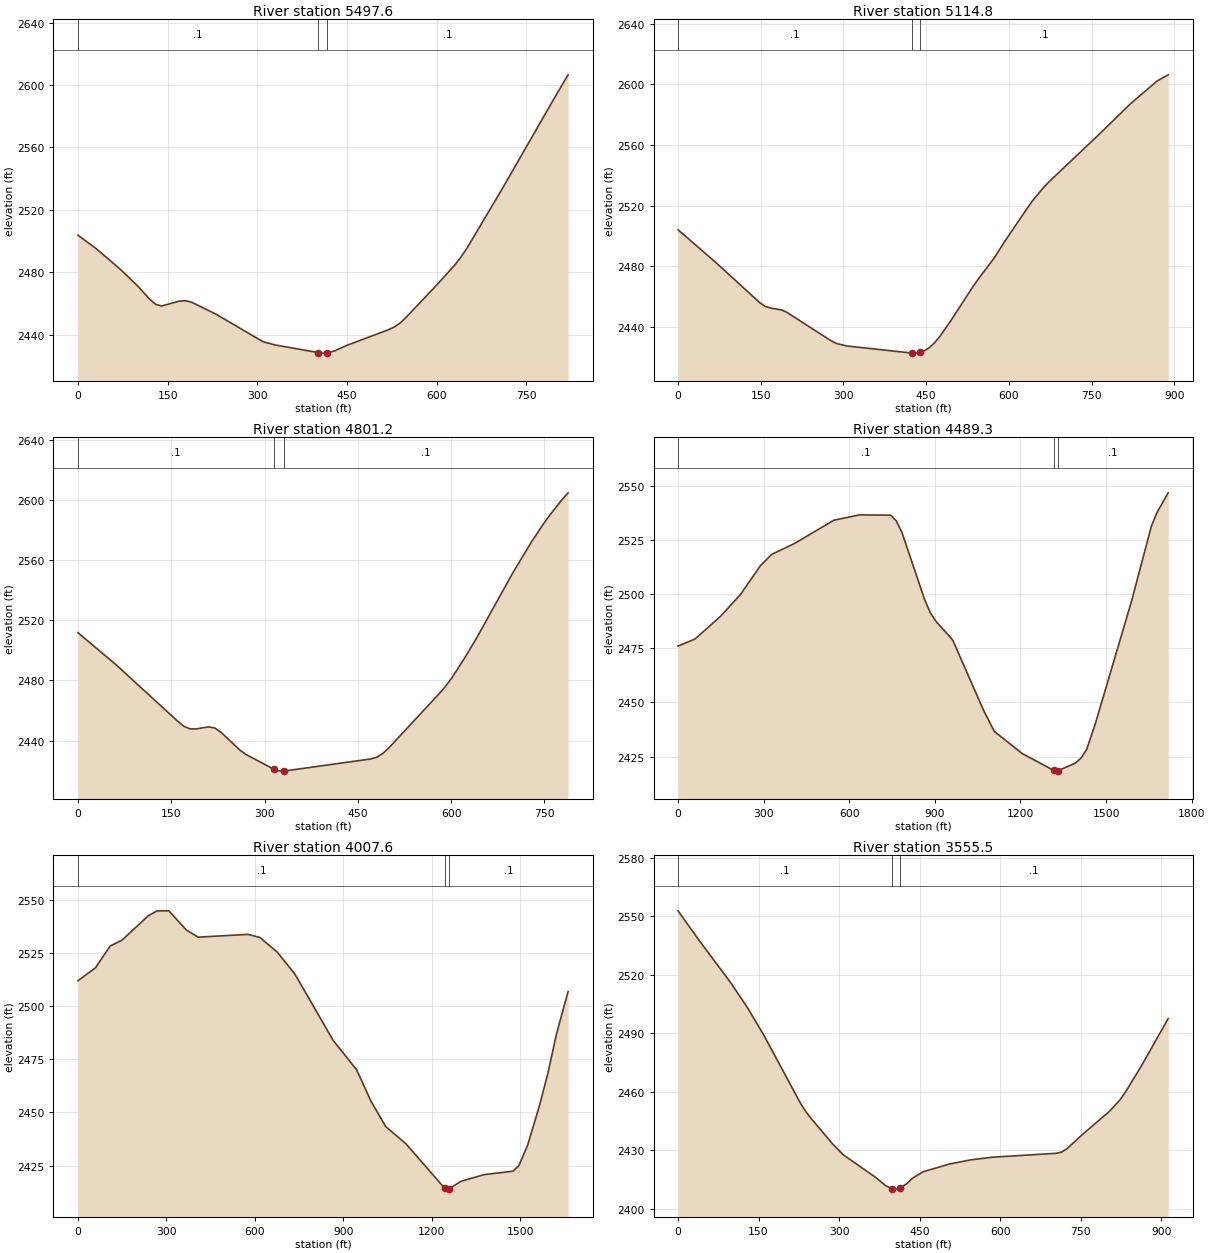
Type RM Length L Ch R = 1 ,5497.6  ,369.2,382.8,396.4
XS GIS Cut Line= 3
     2020469.482      340774.092     2020777.547      340503.963
     2021087.283       340234.91
#Sta/Elev= 30
       0 2503.78      30 2495.35      70 2482.28    99.9  2471.3   119.9 2462.85
   129.9 2459.53   139.9 2458.43   169.9 2461.58   179.9 2461.84   189.9 2460.92
   229.8 2453.45   309.8 2435.52   329.8 2433.48   402.2 2428.57   409.7 2428.24
   417.2  2428.4   429.7 2429.71   449.8  2433.2   519.8 2443.27   529.8 2445.09
   539.8 2447.78   549.8 2451.48   599.8 2471.71   629.9 2484.44   639.9  2489.3
   649.9 2494.93   659.9 2501.32   709.9 2533.56     800 2593.57     820 2606.54
#Mann= 3 , 0 , 0
       0      .1       0   402.2    .045       0   417.2      .1       0
Bank Sta=402.2,417.2
XS Rating Curve= 0 ,0
Exp/Cntr=0.3,0.1

Type RM Length L Ch R = 1 ,5114.8  ,321,313.6,306.1
XS GIS Cut Line= 3
     2020515.643      340876.348     2021114.946      340807.143
     2021398.173      340769.259
#Sta/Elev= 30
       0 2504.01    69.2 2482.23   148.4 2455.85   158.2 2453.44   168.1 2452.35
   187.9 2451.11   197.8 2449.45   276.9 2430.93   286.8 2429.02   306.6 2427.32
   424.2 2422.66   425.3 2422.62   439.2 2423.19     445 2423.83   454.9 2426.01
   464.8 2429.28   474.7 2433.55   494.5  2443.9   534.1 2466.06     544 2471.24
   573.6 2485.49   593.4 2496.82   632.8 2517.95   642.7 2523.03   662.4 2531.72
   672.3  2535.5   760.9 2566.01   820.1 2587.02   869.3 2602.32     889 2606.27
#Mann= 3 , 0 , 0
       0      .1       0   424.2    .045       0   439.2      .1       0
Bank Sta=424.2,439.2
XS Rating Curve= 0 ,0
Exp/Cntr=0.3,0.1

Type RM Length L Ch R = 1 ,4801.2  ,316.8,311.8,306.9
XS GIS Cut Line= 3
     2020647.713      341272.572      2021215.97      340998.366
     2021358.751      340932.728
#Sta/Elev= 30
       0 2511.74    60.1 2490.83   160.2  2452.9   170.3 2449.48   180.3 2447.76
   190.3 2447.74   210.3 2449.07   220.3 2448.27   230.4 2445.33   260.4 2433.62
   270.4 2430.68   315.6 2420.78   320.5    2420   330.5 2419.63   330.6 2419.63
   470.7 2427.72   480.7 2428.88   490.7 2431.54   500.8 2435.49   580.9 2471.17
   590.9 2475.96   600.9 2481.48   620.9 2494.32   640.8    2508   699.7 2551.83
   729.2 2572.05   748.8 2584.29   758.6 2589.88   778.3 2600.15   788.1 2604.74
#Mann= 3 , 0 , 0
       0      .1       0   315.6    .045       0   330.6      .1       0
Bank Sta=315.6,330.6
XS Rating Curve= 0 ,0
Exp/Cntr=0.3,0.1

Type RM Length L Ch R = 1 ,4489.3  ,503.9,481.7,459.5
XS GIS Cut Line= 4
     2020507.001      342445.166     2020801.632      341569.607
     2021019.366      341462.514     2021452.292      341121.037
#Sta/Elev= 30
       0 2475.99    59.6 2479.29     149 2489.76   218.5 2499.75   288.1 2513.03
   327.8  2518.3   407.3 2523.31   546.3 2534.12   635.7 2536.56     745 2536.45
   764.9 2533.82   784.7 2528.45   864.2 2497.46   884.1 2491.41   903.9 2487.42
   962.6  2478.8  1069.4 2446.75  1108.2 2436.65  1205.8 2426.42  1316.8 2418.62
    1324 2418.29  1331.8 2418.47  1392.9 2422.04  1412.6 2424.38  1432.3 2428.37
  1461.8 2439.91  1589.8 2496.97  1658.8 2531.35  1678.4 2537.64  1717.8 2546.75
#Mann= 3 , 0 , 0
       0      .1       0  1316.8    .045       0  1331.8      .1       0
Bank Sta=1316.8,1331.8
XS Rating Curve= 0 ,0
Exp/Cntr=0.3,0.1

Type RM Length L Ch R = 1 ,4007.6  ,453.2,452,450.9
XS GIS Cut Line= 4
     2020961.607       342573.25     2021617.304      341892.933
      2021555.12      341644.195     2021518.612      341184.618
#Sta/Elev= 30
       0 2511.86    59.7 2517.99   109.4 2528.21   149.2 2530.91   238.7 2542.39
   268.5 2544.71   308.3 2544.72     368 2535.69   407.8 2532.35   576.9 2533.66
   616.6 2532.24   676.3 2525.31     736 2514.96   865.3 2483.92   944.9 2470.11
   994.2 2455.23  1043.5 2443.42  1112.5 2435.31  1243.9 2414.37  1250.3    2414
  1258.9 2414.23  1299.4 2417.69  1377.8 2420.82  1475.9 2422.44  1495.5 2425.07
    1525 2434.58  1564.2 2452.68  1593.6 2468.28    1623 2486.91  1662.3 2506.78
#Mann= 3 , 0 , 0
       0      .1       0  1243.9    .045       0  1258.9      .1       0
Bank Sta=1243.9,1258.9
XS Rating Curve= 0 ,0
Exp/Cntr=0.3,0.1

Type RM Length L Ch R = 1 ,3555.5  ,553.7,554.2,554.4
XS GIS Cut Line= 2
     2022045.805      341931.029     2021928.546      341025.426
#Sta/Elev= 30
       0 2552.81    39.7 2537.51    99.3  2515.5     129 2503.29   158.8 2489.56
   228.3 2454.03   238.2 2449.84   248.1 2446.27   287.8 2433.32   307.7 2427.72
   367.2  2416.3   387.1 2411.82   398.7 2410.34     407 2410.09   413.7 2410.68
   426.8 2413.03   436.7 2415.66   456.6    2419   506.2 2422.99   545.9 2425.13
   585.6 2426.45   704.7 2428.47   714.6 2429.08   724.6 2430.81   754.4 2438.36
     804 2450.04   823.8 2456.03   833.8 2459.95   863.5 2473.38   913.2 2497.58
#Mann= 3 , 0 , 0
       0      .1       0   398.7    .045       0   413.7      .1       0
Bank Sta=398.7,413.7
XS Rating Curve= 0 ,0
Exp/Cntr=0.3,0.1

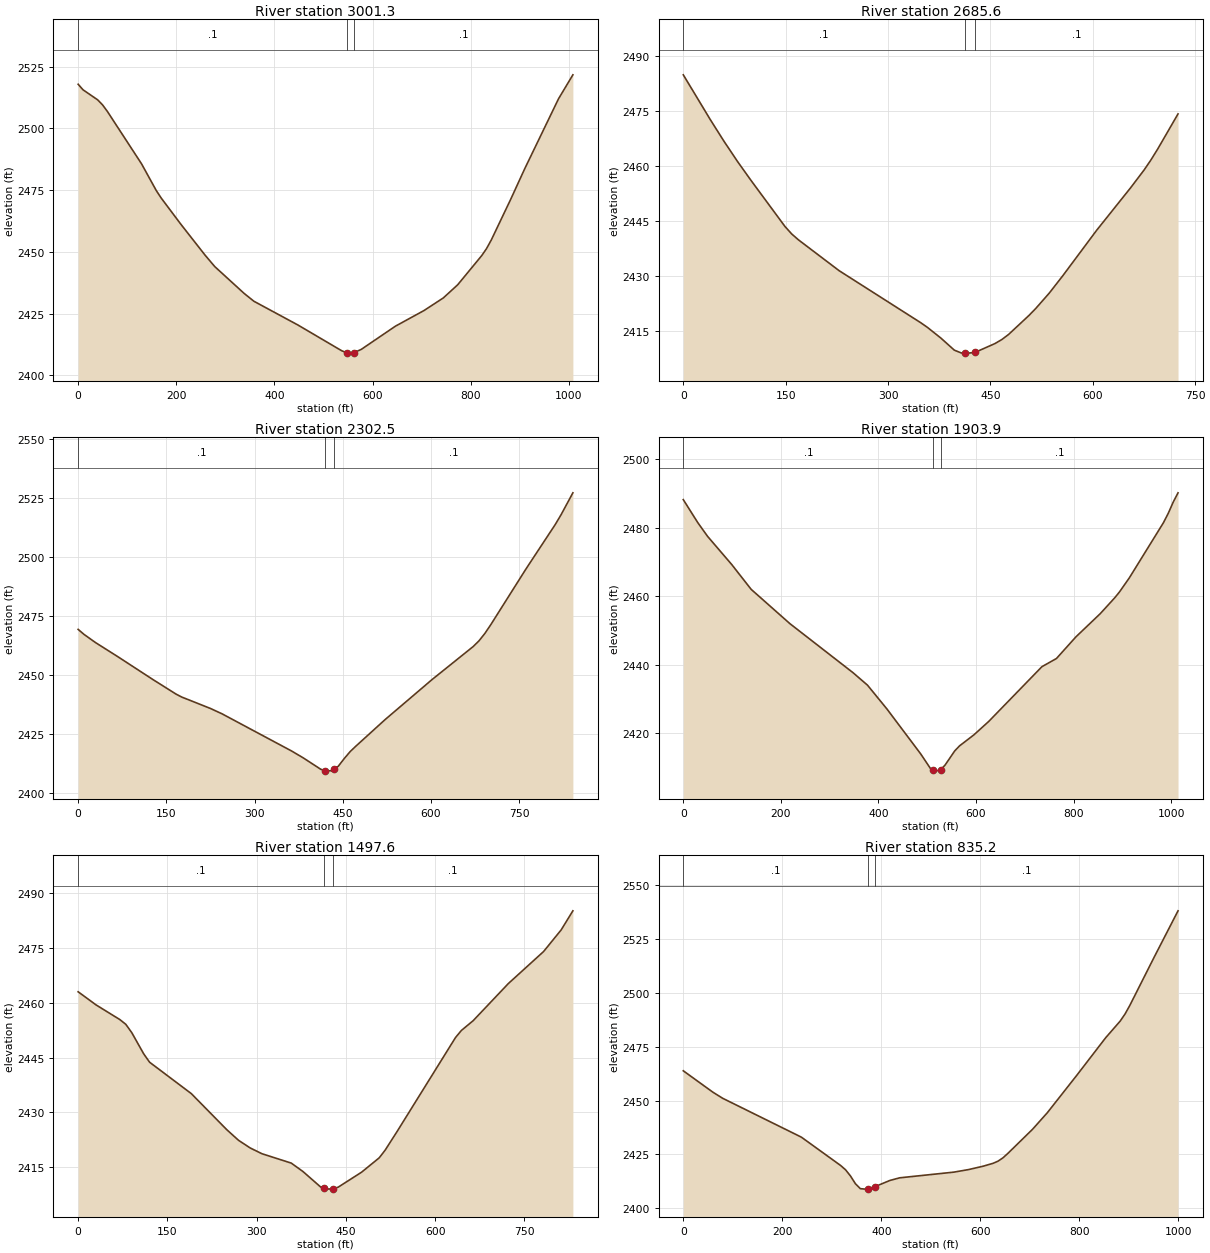
Type RM Length L Ch R = 1 ,3001.3  ,305.2,315.7,326.4
XS GIS Cut Line= 3
     2022594.292      341989.093     2022517.577      341347.306
     2022624.886      341001.974
#Sta/Elev= 30
       0 2517.91     9.9 2515.67    39.8 2511.59    49.7 2509.57    59.7 2506.86
   129.3 2485.64   159.1 2474.89     169 2471.88   208.8 2461.33   258.5 2448.72
   278.4 2444.05   338.1 2433.21     358 2430.03   447.5 2420.43     537 2409.97
   547.3 2409.18   556.9 2409.01   562.3 2409.23   576.8 2410.52   646.4 2419.92
     705  2426.3   744.1 2431.38   773.4 2436.71   822.3 2448.52     832 2451.32
   841.8 2454.86   880.9 2471.14   910.2 2483.83   978.7 2512.01    1008 2521.73
#Mann= 3 , 0 , 0
       0      .1       0   547.3    .045       0   562.3      .1       0
Bank Sta=547.3,562.3
XS Rating Curve= 0 ,0
Exp/Cntr=0.3,0.1

Type RM Length L Ch R = 1 ,2685.6  ,392.4,383.1,373.7
XS GIS Cut Line= 2
     2022673.288      341881.435     2022931.565      341204.021
#Sta/Elev= 30
       0 2484.93    39.7 2472.66    59.6  2466.8    79.4 2461.28    99.3 2456.08
     149 2443.52   158.9 2441.47   168.8 2439.86   228.4 2431.44   347.6 2417.28
   357.5    2416   377.4 2413.05   397.2 2409.74   407.2 2408.99   412.3 2408.96
   417.1 2408.93   427.3 2409.11   456.8 2411.55   466.8 2412.64   476.7 2414.03
   506.5 2419.21   516.4  2421.1   536.3 2425.32   556.2 2430.08   605.8 2442.49
   655.5 2454.08   675.3 2458.95   685.3 2461.69   695.2 2464.66     725 2474.26
#Mann= 3 , 0 , 0
       0      .1       0   412.3    .045       0   427.3      .1       0
Bank Sta=412.3,427.3
XS Rating Curve= 0 ,0
Exp/Cntr=0.3,0.1

Type RM Length L Ch R = 1 ,2302.5  ,380.2,398.4,416.7
XS GIS Cut Line= 3
     2023104.179      342006.789     2023182.319      341673.058
     2023153.569      341175.089
#Sta/Elev= 30
       0 2469.17     9.8 2467.09    29.4 2463.61    68.6 2457.43   127.3 2447.91
   166.5 2441.76   176.3  2440.5   225.2 2435.66   244.8  2433.4   362.7 2417.71
   382.7 2414.78   412.6 2409.93   420.3 2409.31   422.6 2409.13   432.5 2409.39
   435.3  2409.9   442.5  2411.2   452.5  2414.4   462.5 2417.35   472.4  2419.7
   522.3 2430.99   602.1 2447.93     672  2461.9   681.9 2464.33   691.9 2467.46
   701.9 2471.15   761.8 2494.77   811.6  2513.6   821.6 2517.79   841.6 2527.02
#Mann= 3 , 0 , 0
       0      .1       0   420.3    .045       0   435.3      .1       0
Bank Sta=420.3,435.3
XS Rating Curve= 0 ,0
Exp/Cntr=0.3,0.1

Type RM Length L Ch R = 1 ,1903.9  ,424.1,406.3,388.4
XS GIS Cut Line= 3
     2023115.572      342131.272     2023670.642      341534.884
     2023723.969      341342.628
#Sta/Elev= 30
       0 2488.25    29.8 2481.51    49.7 2477.54    99.4 2469.27   139.1 2462.04
   218.6 2452.01   347.8  2437.7   377.6 2434.04   417.3 2427.11   486.8 2413.93
   506.7 2409.68   512.5 2409.24   516.7 2408.92   527.5 2409.33   536.5 2410.66
   556.4 2414.82   566.3  2416.3   596.1 2419.56     626 2423.42   735.2 2439.44
     765 2441.83   804.8 2448.14   854.6 2454.91   884.6 2459.59   894.5 2461.34
   914.5 2465.42   984.3 2481.51   994.3 2484.29  1004.3 2487.52  1014.2 2490.24
#Mann= 3 , 0 , 0
       0      .1       0   512.5    .045       0   527.5      .1       0
Bank Sta=512.5,527.5
XS Rating Curve= 0 ,0
Exp/Cntr=0.3,0.1

Type RM Length L Ch R = 1 ,1497.6  ,654.1,662.4,670.8
XS GIS Cut Line= 3
     2023811.261      342216.906     2023860.091      342002.191
     2023837.144      341391.129
#Sta/Elev= 30
       0 2463.01      30 2459.43    70.1  2455.4    80.1  2454.1    90.1 2451.84
   110.1 2446.05   120.1 2443.73   190.2 2435.14   249.8 2425.27   269.5 2422.37
   289.2 2420.26     309 2418.68   358.3 2416.11     378  2413.8   407.6 2409.58
   413.1 2409.25   417.4 2408.99   428.1 2409.06   437.2 2409.53   476.6 2413.64
   506.2 2417.57   516.1 2419.66   535.8 2424.67   634.4 2450.49   644.3 2452.43
     664 2455.09   723.2 2465.26   782.4 2474.02     812 2479.95   831.7 2485.17
#Mann= 3 , 0 , 0
       0      .1       0   413.1    .045       0   428.1      .1       0
Bank Sta=413.1,428.1
XS Rating Curve= 0 ,0
Exp/Cntr=0.3,0.1

Type RM Length L Ch R = 1 ,835.2   ,541.3,537.4,534
XS GIS Cut Line= 3
      2024162.26      342436.794     2024436.858      341690.653
     2024523.864      341505.414
#Sta/Elev= 30
       0 2463.82    59.6 2453.92    79.5 2451.07   238.5 2433.04     318 2419.87
     328 2417.85   337.9 2414.99   347.8 2411.41   357.8 2409.12   367.7 2408.91
   372.3 2409.07   387.3 2410.06   417.4 2412.93   437.3 2414.16   546.6 2416.79
   576.4 2417.98   606.2 2419.56   626.1  2420.9     636 2421.89     646 2423.44
   655.9  2425.5   705.6 2436.65   735.4 2444.31   795.1 2461.72   853.5 2479.16
   882.8 2486.88   892.5 2490.13   902.3 2494.16     951 2516.33   999.7 2538.05
#Mann= 3 , 0 , 0
       0      .1       0   372.3    .045       0   387.3      .1       0
Bank Sta=372.3,387.3
XS Rating Curve= 0 ,0
Exp/Cntr=0.3,0.1

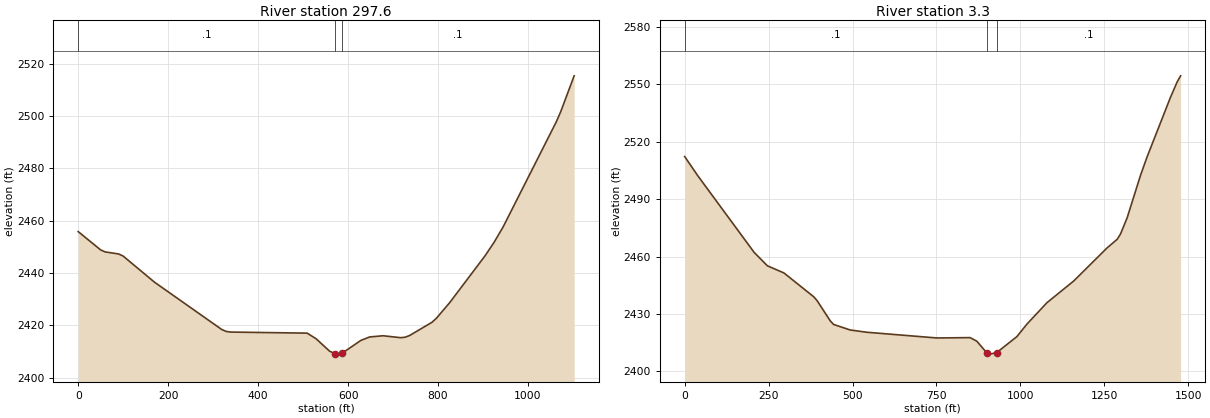
Type RM Length L Ch R = 1 ,297.6   ,301,297.5,293.5
XS GIS Cut Line= 3
     2024717.523      342755.776     2024807.048      342183.883
     2024898.552        341668.2
#Sta/Elev= 30
       0 2455.82    49.9 2448.82    59.9 2448.06    89.8 2447.27    99.8 2446.48
   169.7 2436.46   319.4 2418.34   329.4 2417.61   339.3 2417.39     509 2416.98
     529 2414.82   558.9 2410.08   571.4 2409.08   578.9 2408.95   586.4 2409.25
   628.3 2414.19     648 2415.52   677.7 2415.98   717.2 2415.24   727.1 2415.44
     737 2416.09   786.4 2421.12   796.3 2422.67   825.9 2428.64     905 2446.68
   924.7 2451.76   944.5 2457.55  1063.1 2497.89    1073 2501.81  1102.6 2515.42
#Mann= 3 , 0 , 0
       0      .1       0   571.4    .045       0   586.4      .1       0
Bank Sta=571.4,586.4
XS Rating Curve= 0 ,0
Exp/Cntr=0.3,0.1

Type RM Length L Ch R = 1 ,3.3     ,6.4,3.3,0
XS GIS Cut Line= 4
     2024748.868      343072.611      2025045.79      342583.902
     2025093.992      342229.182     2025374.241      341758.825
#Sta/Elev= 30
       0 2512.22    39.4 2502.12     207 2462.14   246.5 2455.14   295.8  2451.4
   384.5 2438.96   394.4 2436.96   433.8 2426.35   443.7  2424.5     493 2421.62
   542.3 2420.43   750.8 2417.45   850.3 2417.62   870.2 2415.76     900 2409.66
   909.9    2409   929.8 2409.85   989.6 2418.16  1019.4 2424.66  1079.1 2435.87
  1158.8  2447.2  1258.3 2464.51  1288.2 2468.96  1298.2 2471.74  1318.1 2480.27
  1357.9 2502.44  1377.8 2512.22  1447.5 2543.34  1467.4 2551.36  1477.3  2554.4
#Mann= 3 , 0 , 0
       0      .1       0     900    .045       0   929.8      .1       0
Bank Sta=900,929.8
XS Rating Curve= 0 ,0
Exp/Cntr=0.3,0.1

Chan Stop Cuts=-1
Use User Specified Reach Order=0
Composite Channel Slope=5